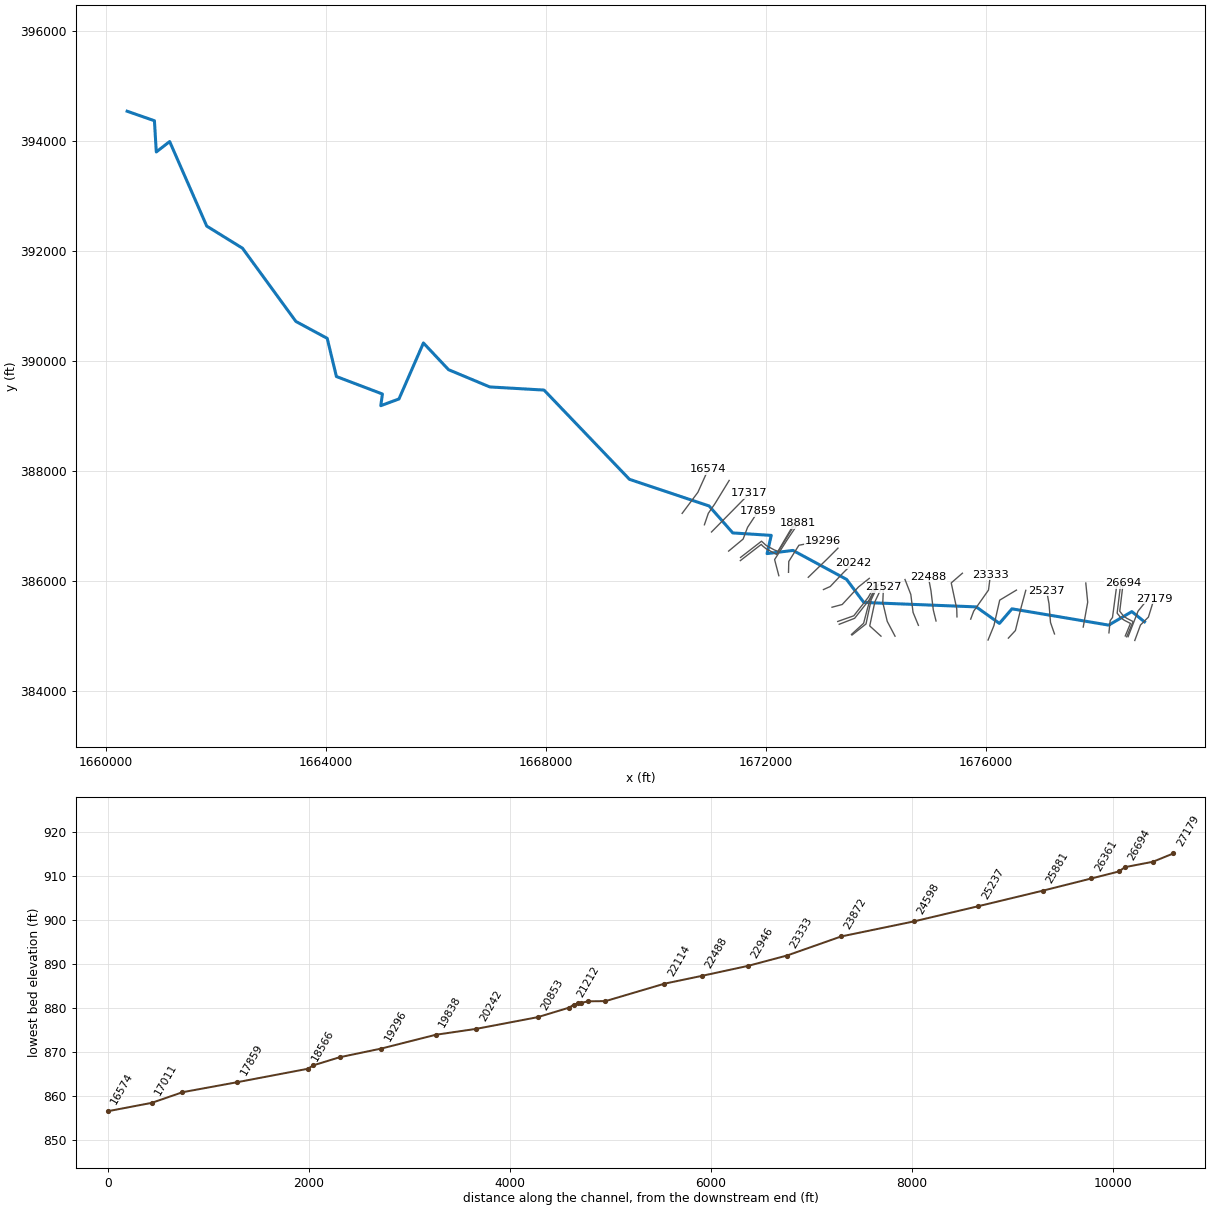
--- NFKFSHNGCK_M.prj (project) ---

Proj Title=NFKFSHNGCK_M
Current Plan=p01
Default Exp/Contr=0,0
English Units
Geom File=g01
Flow File=f01
Plan File=p01
BEGIN DESCRIPTION:
---------- MODELED AS PART OF WVEMD CTP PROGRAM, 2023----------
Stream Name: North Fork Fishing Creek Middle Reach
Flood Zone:  AFH
Wetzel County, WV
HEC-RAS Version: RAS 6.3
Vertical Datum: NAVD88
Projection: NAD 1983 StatePlane West Virginia S FIPS 4702 (US Feet)
Terrain: 1-meter West Virginia FEMA R3 South Central (collected 2018-2020)
Land Use: 2019 NLCD
Hydrologic Method:
WV SIR2010-5033 regression equations
Additional Model Notes:
Model was originally NFKFSHINGCK, but there were 2 dominant flow path issues with WILLEYFK and WILEYFK, so the model was split into three reaches. The US-most XS is used as a shared XS with WILEYFK.
There is a coincident peak with WILLEYFK; KWSEL tie-in used. DS XS is shared XS with NFKFSHNGCK_L.
END DESCRIPTION:
DSS Export Rating Curves= 0
DSS Export Rating Curve Sorted= 0
DSS Export Volume Flow Curves= 0
DXF OffsetX= 0
DXF OffsetY= 0
DXF ScaleX= 0
DXF ScaleY= 0

--- NFKFSHNGCK_M.p01 (plan) ---

Plan Title=Floodplain
Program Version=6.31
Short Identifier=Floodplain
Geom File=g01
Flow File=f01
Subcritical Flow
K Sum by GR= 0
Std Step Tol= 0.01
Critical Tol= 0.01
Num of Std Step Trials= 20
Max Error Tol= 0.3
Flow Tol Ratio= 0.001
Split Flow NTrial= 30
Split Flow Tol= 0.02
Split Flow Ratio= 0.02
Log Output Level= 0
Friction Slope Method= 1
Unsteady Friction Slope Method= 2
Unsteady Bridges Friction Slope Method= 1
Parabolic Critical Depth
Global Vel Dist= 0 , 0 , 0
Global Log Level= 0
CheckData=True
Encroach Param=-1 ,0,0, 0
Mapping Interval=1HOUR
Computation Time Step Use Courant=        0
Computation Time Step Use Time Series=    0
Computation Time Step Count To Double=0
Computation Time Step Max Doubling=0
Computation Time Step Max Halving=0
Computation Time Step Residence Courant=0
Run HTab= 0
Run UNet= 0
Run Sediment= 0
Run PostProcess= 0
Run WQNet= 0
Run RASMapper= 0
UNET Theta= 0
UNET Theta Warmup= 0
UNET ZTol= 0
UNET ZSATol= 0
UNET MxIter= 0
UNET Max Iter WO Improvement= 0
UNET MaxInSteps= 0
UNET DtIC= 0
UNET DtMin= 0
UNET MaxCRTS= 0
UNET WFStab= 0
UNET SFStab= 0
UNET WFX= 1
UNET SFX= 1
UNET Gravity=32.17405
UNET 1D Methodology=Finite Difference
UNET DSS MLevel= 1
UNET Pardiso=0
UNET DZMax Abort= 0
UNET Use Existing IB Tables= 0
UNET Froude Reduction=False
UNET Froude Limit= 0
UNET Froude Power= 0
UNET D1 Cores= 0
UNET WindReference=Eulerian
UNET WindDragFormulation=Hsu (1988)
UNET D2 Coriolis=0
UNET D2 Cores= 0
UNET D2 Theta= 1
UNET D2 Theta Warmup= 1
UNET D2 Z Tol= 0.01
UNET D2 Volume Tol= 0.01
UNET D2 Max Iterations= 20
UNET D2 Equation= 0
UNET D2 RampUpFraction=0.1
UNET D2 TimeSlices= 1
UNET D2 Turbulence Formulation=Non-Conservative (original)
UNET D2 Eddy Viscosity=0.3
UNET D2 Transverse Eddy Viscosity=0.1
UNET D2 Smagorinsky Mixing=0
UNET D2 BCVolumeCheck=0
UNET D2 Cores=0
UNET D2 SolverType=PARDISO (Direct)
UNET D2 Minimum Iterations= 3
UNET D2 Maximum Iterations= 30
UNET D2 Restart Number= 10
UNET D2 Relaxation Coeff=1.3
UNET D2 SOR Precondition Iterations= 10
UNET D2 ILUT Maximum Fill= 8
UNET D2 ILUT Tolerance=1E-08
UNET D2 Convergence Tolerance=0.00001
UNET D1D2 MaxIter= 0
UNET D1D2 ZTol=0.01
UNET D1D2 QTol=0.1
UNET D1D2 MinQTol=1
Write IC File= 0
Write IC File at Fixed DateTime=0
Write IC File at Sim End=0
Echo Input=False
Echo Parameters=False
Echo Output=False
Write Detailed= 0
HDF Write Warmup=0
HDF Write Time Slices=0
HDF Flush=0
HDF Compression= 1
HDF Chunk Size= 1
HDF Spatial Parts= 1
HDF Use Max Rows=0
HDF Fixed Rows= 1
Calibration Method= 0
Calibration Iterations= 20
Calibration Max Change=0.05
Calibration Tolerance=0.2
Calibration Maximum=1.5
Calibration Minimum=0.5
Calibration Optimization Method= 1
WQ AD Non Conservative
WQ ULTIMATE=-1
WQ Max Comp Step=1HOUR
WQ Output Interval=15MIN
WQ Output Selected Increments= 0
WQ Create Restart=0
WQ Fixed Restart=0
WQ System Summary=0
WQ Write To DSS=0
Sorting and Armoring Iterations= 10
XS Update Threshold= 0.02
Bed Roughness Predictor= 0
Hydraulics Update Threshold= 0.02
Energy Slope Method= 1
Volume Change Method= 1
Sediment Retention Method= 0
Sediment TS Multiplier= 1
Warm Up Method= 0
XS Weighting Method= 0
Number of US Weighted Cross Sections= 1
Number of DS Weighted Cross Sections= 1
Upstream XS Weight=0
Main XS Weight=1
Downstream XS Weight=0
Number of DS XS's Weighted with US Boundary= 1
Upstream Boundary Weight= 1
Weight of XSs Associated with US Boundary= 0
Number of US XS's Weighted with DS Boundary= 1
Downstream Boundary Weight= 0.5
Weight of XSs Associated with DS Boundary= 0.5
Percentile Method= 0
Sediment Output Level= 3
Mass or Volume Output= 0
Output Increment Type= 1
Profile and TS Output Increment= 1
Transport Output Increment 1
XS Output Flag= 0
XS Output Increment= 10
Read HDF5 Sediment Hotstart= 0
Sediment Hotstart Type= 0
Write Gradation File= 0
Read Gradation Hotstart= 0
Write HDF5 File= 1
Write Binary Output= 1
Write DSS Sediment File= 0
DSS Sediment Output Type= 1
SV Curve= 0
Specific Gage Flag= 0
Subcell Erosion Methods= 0
Subcell Deposition Methods= 0
Advection Scheme= 1
Matrix Solver= 0
Implicit Weighting Factor= 1
Maximum Outer Loop Convergence Iterations= 5
Convergence Maximum Absolute= 0.001
Convergence RMSE= 0.0001
Grain Fractions Max Abs Error= 0.001
Max Subgrid Regions= 1
Max Subgrid Length Scale= 3.402823E+38
Initial Layer Thickness= 3.402823E+38
Min Layer Thickness= 3.402823E+38
Max Layer Thickness= 3.402823E+38
Number of Layers= 5

--- NFKFSHNGCK_M.f01 (steady flow) ---

Flow Title=Flow
Program Version=6.31
Number of Profiles= 1
Profile Names=F01pct
River Rch & RM=NFKFSHNGCK_M,Main            ,27179
    1940
River Rch & RM=NFKFSHNGCK_M,Main            ,20242
    2240
River Rch & RM=NFKFSHNGCK_M,Main            ,15634
    2500
River Rch & RM=NFKFSHNGCK_M,Main            ,10565
    2800
River Rch & RM=NFKFSHNGCK_M,Main            ,931
    5310
River Rch & RM=NFKFSHNGCK_M,Main            ,0
    6230
Boundary for River Rch & Prof#=NFKFSHNGCK_M,Main            , 1
Up Type= 0
Dn Type= 1
Dn Known WS=806
DSS Import GetInterval= 0
DSS Import GetPeak= 0
DSS Import FillOption= 0

--- NFKFSHNGCK_M.g01 (geometry) ---

Geom Title=Geometry
Program Version=6.31

River Reach=NFKFSHNGCK_M    ,Main
Reach XY= 30
1678890.50099673385252.9220088291678660.34657533 385438.61686045
1678239.25811122385192.737807897 1676479.6321007385489.253816081
1676251.11184617385223.9017056181675828.87099673385524.619008871
1673784.37799669385605.348008849 1673470.3239967386025.537008868
1672495.59701801386552.1513553761672024.15499674386494.712008873
1672100.89899672386826.1830088821671400.94599671386870.814008817
1670970.26545469387361.2979808341669521.11599669387846.788008872
1667967.34799671389471.1440088441666980.93923537389528.234247511
1666230.73299671389841.9390088171665773.19199673390328.395008836
1665328.40799668389309.5590088321664997.58399669389187.094008816
1665027.60626507389399.4908189021664190.50899672389717.774008805
1664022.96999671390412.5900088351663453.16999672390720.452008882
 1662481.9589967392053.1040088771661831.36599674392456.216008851
1661156.96099671393994.6760088531660913.73299674393805.877008864
1660879.71499672394373.9760088041660383.42283906394546.952185535

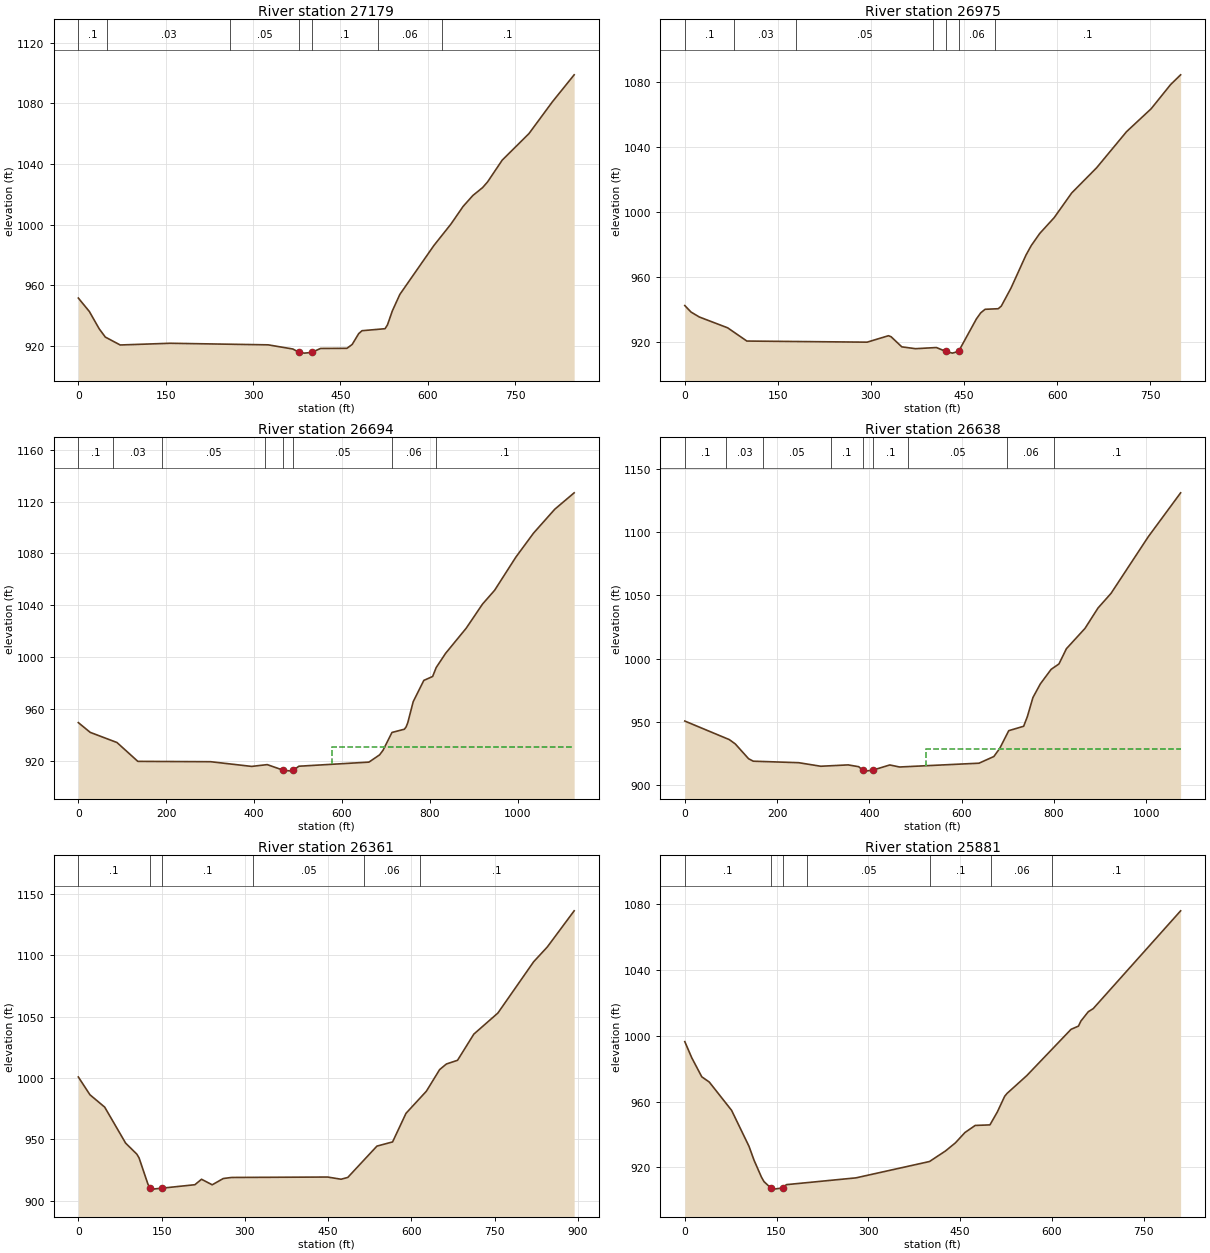
Type RM Length L Ch R = 1 ,27179   ,196.4,203.6,205.8
XS GIS Cut Line= 4
1678713.56641098384913.0828725371678817.47807282385194.701507787
 1678961.4391846385338.6599272721679064.52874707385670.669212739
#Sta/Elev= 30
       0  951.54    18.9  942.69    35.8  931.28    46.3  925.82    71.9  920.59
   157.6  921.72     326  920.68   368.4  917.93  379.41 915.654   388.2  915.22
  400.57915.6547   415.9   918.3   461.2  918.39   470.2  920.93   481.5  928.11
   487.2  930.01   526.7  931.32   530.9  933.91   539.2  943.08   552.1  953.95
   610.4  986.12   639.8 1000.32   660.8 1012.01   677.5 1019.19   694.2 1024.39
   702.6 1028.07   727.9 1042.52   773.8    1060   814.2 1081.05   851.4 1098.76
#Mann= 7 ,-1,0
       0      .1       0      50     .03       0     260     .05       0
  379.41    .045       0  400.57      .1       0  513.77     .06       0
  623.77      .1       0
Bank Sta=379.41,400.57
XS Rating Curve= 0 ,0
Exp/Cntr(USF)=0,0
Exp/Cntr=0.3,0.1

Type RM Length L Ch R = 1 ,26975   ,263.6,280.8,293.3
XS GIS Cut Line= 3
1678592.46883098384982.7278165731678773.84778668385448.357374494
1678961.99461386385681.172153455
#Sta/Elev= 30
       0  942.56      10  938.58    23.4  935.53    69.1  928.87     100  920.74
   293.8  920.06   328.2  924.02   332.5  923.37   349.7  917.18   371.8  916.05
   405.5  916.76  420.48914.3856   431.2  913.32  441.19 914.386   469.9  934.34
   476.9  938.09   483.9  940.26   505.1  940.62     510  942.22   525.7  953.34
   549.8  973.58   558.3  979.44   571.9  986.85   595.3  996.63   623.4 1011.74
   663.6 1027.24   711.9 1049.47   751.5 1063.53   782.8 1078.38     799 1084.39
#Mann= 7 ,-1,0
       0      .1       0      80     .03       0     180     .05       0
     400     .06       0  420.48    .045       0  441.19     .06       0
  499.71      .1       0
Bank Sta=420.48,441.19
XS Rating Curve= 0 ,0
Exp/Cntr(USF)=0,0
Exp/Cntr=0.3,0.1

Type RM Length L Ch R = 1 ,26694   ,55.1,56,55.1
XS GIS Cut Line= 6
1678565.87521931384979.6145147721678682.63633231385257.364788289
1678572.05218289385314.4004775861678511.89332528385354.506382661
1678440.03691202 385444.744669081678501.82836069385956.353888809
#Sta/Elev= 30
       0   949.5      27  941.99      88  934.15   135.5  919.61   301.3  919.34
   394.6  915.72   430.1   917.1  466.88912.7658   487.3  912.08  489.64912.7638
   502.1  915.86   661.7  919.03   685.9  924.63   693.9  928.25   714.1  941.91
   742.3   944.4   746.3  946.19   750.1  949.45   762.4  965.63   786.6  982.06
   806.7   985.1   814.8     992   836.3 1002.99   883.1 1022.33   920.3 1040.97
   947.8 1051.59   996.1 1077.13  1036.4 1095.68  1084.8 1114.13  1128.9 1126.77
#Mann= 8 ,-1,0
       0      .1       0      80     .03       0     190     .05       0
  425.72      .1       0  466.88    .045       0  489.64     .05       0
  713.56     .06       0  813.56      .1       0
#XS Ineff= 1 ,-1
   578.11128.889  930.45
Permanent Ineff=
       F
Bank Sta=466.88,489.64
XS Rating Curve= 0 ,0
Exp/Cntr(USF)=0,0
Exp/Cntr=0.3,0.1

Type RM Length L Ch R = 1 ,26638   ,284.3,276.9,259.6
XS GIS Cut Line= 6
1678540.24821089 384995.578612211678635.35213515385223.246636765
1678524.76798573385280.2823260621678464.60912811385320.388231137
1678392.75271485385410.6265175561678454.54416353385922.235737285
#Sta/Elev= 30
       0  950.68    96.4  936.03   109.4   932.6   138.2  920.91   148.4  918.97
   246.7  917.79   294.6  914.97   353.9  916.04   376.8  914.62  385.35911.9681
   391.2  911.12  407.88 911.967   444.2  915.99   465.3  914.38   637.5  917.39
   669.7  922.68   682.4  929.11   701.9  943.08   734.2  946.56   742.2  954.17
   754.3  969.26   770.4  980.06   793.8  991.56   810.7  995.79   826.8 1007.81
   867.1 1023.88   895.3 1039.98   923.5 1051.54  1004.1 1096.23  1074.3 1130.98
#Mann= 9 ,-1,0
       0      .1       0      90     .03       0     170     .05       0
  316.73      .1       0  385.35    .045       0  407.88      .1       0
  483.46     .05       0     699     .06       0     799      .1       0
#XS Ineff= 2 , 0
                          523.05          928.97
Permanent Ineff=
       F       F
Bank Sta=385.35,407.88
XS Rating Curve= 0 ,0
Exp/Cntr(USF)=0,0
Exp/Cntr=0.3,0.1

Type RM Length L Ch R = 1 ,26361   ,480.5,480,479
XS GIS Cut Line= 4
1678243.24666254385051.7601056831678266.25742558 385275.09986457
1678308.21822876385331.9499850141678386.72553794385924.815526786
#Sta/Elev= 30
       0 1000.85    20.9  986.37    47.5  976.29    85.2  946.98   105.3  938.06
   109.4  934.95   125.4  913.56  129.36910.2858   133.5  909.51  150.48 910.286
   209.9  913.09   221.9  917.55   241.2  913.03   261.1  918.15     276  919.01
   449.1  919.35   473.3  917.57   485.4  919.03   537.9  944.54   566.1  947.96
   590.3  971.26     627  989.27   650.8 1006.82     663 1011.41   683.1 1014.43
   712.5 1035.76   755.8 1052.91   820.3 1094.72   844.8  1106.7   893.2 1136.16
#Mann= 6 ,-1,0
       0      .1       0  129.36    .045       0  150.48      .1       0
  315.18     .05       0  515.18     .06       0  615.18      .1       0
Bank Sta=129.36,150.48
XS Rating Curve= 0 ,0
Exp/Cntr(USF)=0,0
Exp/Cntr=0.3,0.1

Type RM Length L Ch R = 1 ,25881   ,642.1,644.4,647.4
XS GIS Cut Line= 3
1677775.67098605385157.2057326031677857.20942659385610.500456433
1677822.54580735385958.707290695
#Sta/Elev= 30
       0  996.45    11.5  986.54    27.8  975.05      40  971.88    76.5  954.66
     105  932.76   113.1  924.43   125.3  914.05   129.4  911.35   140.5907.4979
   145.6  906.75  160.58907.4966     166  909.47   279.8   913.6     400  923.54
   426.1  929.95   442.3  934.87   457.9  941.16   474.7  945.48   498.8  945.82
   510.9  953.69   522.9  963.23   526.9     965   559.1  975.82   631.4 1003.94
   643.5 1005.89   647.5 1008.98   659.6 1014.65   667.6 1016.51   810.5    1076
#Mann= 7 ,-1,0
       0      .1       0   140.5    .045       0  160.58      .1       0
     200     .05       0     400      .1       0  500.57     .06       0
  600.57      .1       0
Bank Sta=140.5,160.58
XS Rating Curve= 0 ,0
Exp/Cntr(USF)=0,0
Exp/Cntr=0.3,0.1

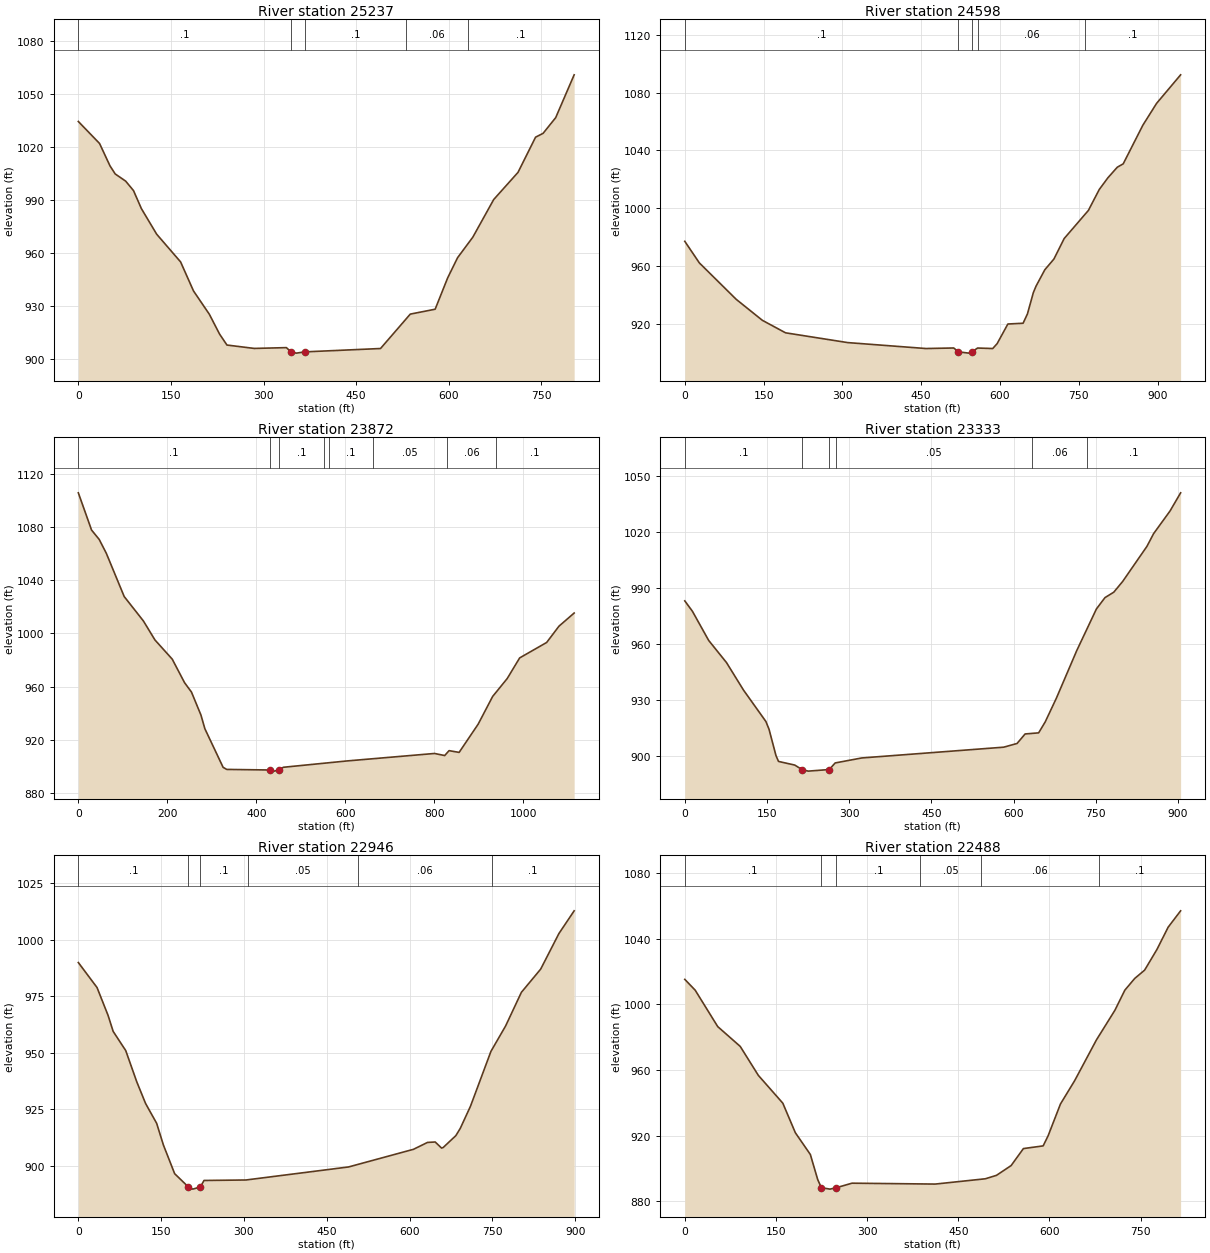
Type RM Length L Ch R = 1 ,25237   ,639.4,638.7,628.9
XS GIS Cut Line= 4
1677253.32173015385032.0976301521677180.42227845385241.191913866
 1677153.6850084385580.4210276261677109.82591984385818.035057716
#Sta/Elev= 30
       0 1034.31    34.4 1021.86    51.3 1009.19    59.8  1004.6    76.7 1000.55
    89.4  995.19   102.1  985.04   126.9  970.53   165.7  954.82   186.6   938.4
   212.3  925.18   228.8     914   240.8  907.77     285  905.86   337.1  906.31
  344.56903.9073   353.2   903.2  366.91 903.908   489.6  905.81   537.8  925.28
   578.1  928.05   598.4  945.81   614.4  957.19   639.1  968.82     673  990.15
   712.3 1005.49   740.8 1025.43     753 1027.61   773.4 1036.49   803.3 1060.72
#Mann= 5 ,-1,0
       0      .1       0  344.56    .045       0  366.91      .1       0
  531.44     .06       0  631.72      .1       0
Bank Sta=344.56,366.91
XS Rating Curve= 0 ,0
Exp/Cntr(USF)=0,0
Exp/Cntr=0.3,0.1

Type RM Length L Ch R = 1 ,24598   ,719.6,726.2,722.5
XS GIS Cut Line= 4
1676414.18370973384956.216618636  1676542.069956385094.136928591
1676649.01903621385525.2754081481676730.73819062 385826.00929339
#Sta/Elev= 30
       0  977.13    27.7   962.2    97.8  937.01   147.7  922.45   191.8  913.81
   310.1  907.04   459.2  902.93     512  903.31     521900.6006   540.9  899.75
   546.4900.5975   557.4  903.27   586.2  902.93   594.6  906.31     615   919.9
     644  920.43   652.3   926.9   663.5  941.62   668.8  946.21   685.4  957.46
   702.7  964.88   722.2  979.05   768.3  998.51     789    1013   805.6 1021.17
   823.3 1028.41   834.6 1030.76   872.1 1057.56   898.2 1072.64   943.9 1092.37
#Mann= 5 ,-1,0
       0      .1       0     521    .045       0   546.4      .1       0
  558.09     .06       0  762.29      .1       0
Bank Sta=521,546.4
XS Rating Curve= 0 ,0
Exp/Cntr(USF)=0,0
Exp/Cntr=0.3,0.1

Type RM Length L Ch R = 1 ,23872   ,535.9,539.2,526.7
XS GIS Cut Line= 4
1676044.37514126384921.0645729381676151.03738152385182.704135632
1676256.31538235385647.2642027511676561.06638788385830.466654584
#Sta/Elev= 30
       0 1105.89    29.7 1077.88    46.9  1070.8    62.9 1060.36   103.1 1027.78
   146.3 1009.39   172.2   995.1   211.1  980.63   238.7  962.96   254.3  955.85
   275.6  938.56   284.4  928.27   325.4  899.18   333.6   897.6  430.82 897.163
   440.3  896.31  450.75897.1628   460.8  899.21   604.3  903.99   800.7  909.61
   823.5  908.04   833.3  911.74   855.9  910.41   898.7  931.65   931.3  952.54
     964  966.02     992  981.56  1052.7   993.2  1080.3 1005.43  1114.5 1015.37
#Mann= 8 ,-1,0
       0      .1       0  430.82    .045       0  450.75      .1       0
  552.55     .05       0  562.55      .1       0  662.55     .05       0
  828.89     .06       0  938.89      .1       0
Bank Sta=430.82,450.75
XS Rating Curve= 0 ,0
Exp/Cntr(USF)=0,0
Exp/Cntr=0.3,0.1

Type RM Length L Ch R = 1 ,23333   ,359.3,386.5,394.6
XS GIS Cut Line= 4
1675728.77690088385302.0122364671675783.43333992385447.645415637
1676052.52141826385831.1042461781676088.17940733 386109.37716427
#Sta/Elev= 30
       0  983.26    13.9  977.69    43.6  962.04      76  950.21   107.1  935.43
     148  918.56   153.7   914.4   166.4  900.26     171  897.17   200.6  895.22
   214.1  892.77   225.1  891.97   263.5  892.82   274.4  896.36   322.8  899.03
   581.8  904.81   606.2   906.8   620.9   911.9   645.6  912.49   657.7  918.45
   677.9  931.07   715.2  956.68     751  978.94   766.6  985.01   782.7  987.93
   798.9  993.69   843.2 1012.52   855.3 1019.31   885.2 1031.42   904.6  1041.2
#Mann= 6 ,-1,0
       0      .1       0   214.1    .045       0   263.5      .1       0
  275.55     .05       0  634.01     .06       0  734.01      .1       0
Bank Sta=214.1,263.5
XS Rating Curve= 0 ,0
Exp/Cntr(USF)=0,0
Exp/Cntr=0.3,0.1

Type RM Length L Ch R = 1 ,22946   ,457.1,458.4,455.1
XS GIS Cut Line= 4
 1675479.0798152385342.6644687891675474.95293711385489.461351094
1675374.68817443385961.0770866991675577.86322068386137.635828861
#Sta/Elev= 30
       0  989.85    33.9  978.79    53.9  966.45    63.1  959.39    85.9  950.89
   105.9  937.06   121.9  927.47   141.9  918.72   154.1  909.15   174.5  896.45
   199.5890.5543   207.3  889.62  220.98890.5544   227.7  893.45   303.6  893.66
   489.4  899.42   607.1  907.23   632.5  910.27   646.5  910.47     658  907.78
   660.8     908   683.9  913.28     692  916.54   710.4  926.29   747.5  950.58
     774  961.78   802.6  976.66   837.6  986.95   870.6 1002.67   898.2 1012.72
#Mann= 6 ,-1,0
       0      .1       0   199.5    .045       0  220.98      .1       0
  306.85     .05       0  506.85     .06       0  749.01      .1       0
Bank Sta=199.5,220.98
XS Rating Curve= 0 ,0
Exp/Cntr(USF)=0,0
Exp/Cntr=0.3,0.1

Type RM Length L Ch R = 1 ,22488   ,374,374.5,374.5
XS GIS Cut Line= 4
1675098.19876607385267.978785771 1675048.3070053385469.013233599
1675005.75226817385821.190368481 1674958.1976429386070.688645542
#Sta/Elev= 30
       0 1015.17    17.1 1008.59    54.2  986.39    91.2  974.33     121  956.69
   161.3  939.73   181.9  921.73   206.6  908.46   218.7  893.19   224.7  888.23
   238.9  887.35   249.6  888.23   275.1  890.97   412.1  890.43   494.5  893.65
   512.9  895.75     537  901.71   557.2  912.06   589.7   913.7   597.9  919.89
   618.2  939.25   641.4  953.36   677.4  978.31   707.8  996.37   724.1 1008.59
   740.4 1015.75   756.7 1020.82     777 1033.46   795.4 1046.98   815.9 1056.95
#Mann= 6 ,-1,0
       0      .1       0   224.7    .045       0   249.6      .1       0
  387.13     .05       0  487.13     .06       0  681.87      .1       0
Bank Sta=224.7,249.6
XS Rating Curve= 0 ,0
Exp/Cntr(USF)=0,0
Exp/Cntr=0.3,0.1

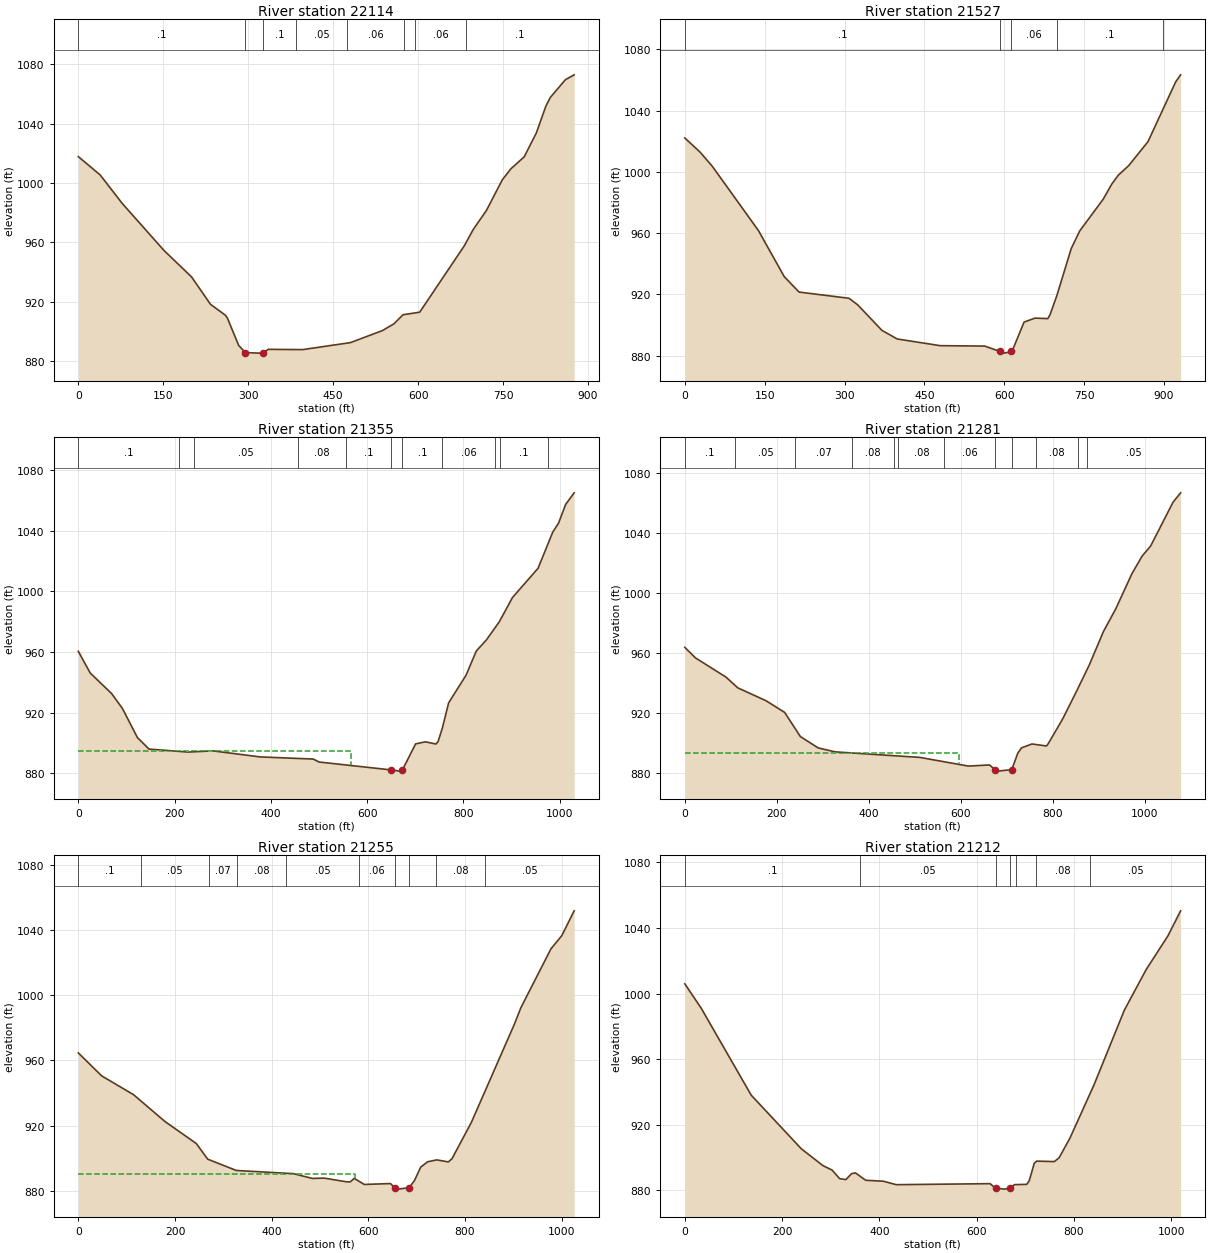
Type RM Length L Ch R = 1 ,22114   ,586,586.9,583.7
XS GIS Cut Line= 4
1674777.67320946385188.8673321311674680.26185507385424.474930833
1674639.41324805385751.263787001 1674533.7952803386022.722080054
#Sta/Elev= 30
       0 1017.74    38.6 1005.39    77.6  986.21     151  954.73     200   936.8
   233.4   918.4   259.5  911.11   263.1  909.29   283.2  890.72  295.09 885.918
   319.4  885.56  326.09885.9169   335.6  888.11   396.1  887.92   480.8  892.65
   537.2  900.76   557.3  905.25   573.5   911.4   602.8  913.08   681.6  957.72
   697.2  968.61   720.7  981.53   748.7 1002.14   763.9 1009.54   787.4 1017.59
   808.8 1033.63   825.7 1051.72   833.6 1057.57   860.3 1069.53   875.6 1072.74
#Mann= 8 ,-1,0
       0      .1       0  295.09    .045       0  326.09      .1       0
  384.95     .05       0  474.95     .06       0  574.95      .1       0
  594.28     .06       0  684.28      .1       0
Bank Sta=295.09,326.09
XS Rating Curve= 0 ,0
Exp/Cntr(USF)=0,0
Exp/Cntr=0.3,0.1

Type RM Length L Ch R = 1 ,21527   ,176.1,172,166.3
XS GIS Cut Line= 4
1674352.50155354384991.1195641851674210.40260957385261.088858147
1674129.58828247385605.5213417391674141.59389506385877.794679969
#Sta/Elev= 30
       0 1022.16    28.7 1012.93    51.7 1003.64   138.2  961.74   186.9  931.53
   214.6  921.48   308.6  917.42   325.1  913.04   370.3  896.46     399  890.84
   479.6  886.47   563.4  886.19   592.3882.6567   600.3  881.59  613.34882.6586
   616.8  884.51   637.3  901.87   657.9  904.46   681.9  904.15   685.9  906.55
   698.7  918.93   725.9  949.89     742   961.5     786  982.18     802  991.99
     814  997.71   834.1 1004.19   870.1 1019.76   922.1 1058.78   931.4 1063.41
#Mann= 5 ,-1,0
       0      .1       0   592.3    .045       0  613.34     .06       0
  698.87      .1       0  898.87     .05       0
Bank Sta=592.3,613.34
XS Rating Curve= 0 ,0
Exp/Cntr(USF)=0,0
Exp/Cntr=0.3,0.1

Type RM Length L Ch R = 1 ,21355   ,73.6,73.6,74.4
XS GIS Cut Line= 4
1674096.98085327384991.9889345451673891.90510931385178.029043764
1673985.81217327385617.6978403381674115.48553161385892.344227233
#Sta/Elev= 30
       0  960.48    24.6   946.2      69   932.7    91.6  922.83   122.8  903.64
     147  896.05     228   894.1   279.5  894.89   377.6  890.91   488.1   889.5
   500.3  887.54  649.54882.3694     668  881.55   673.5  882.37   700.7  899.48
   721.2  900.85   742.9   899.4   747.3  900.89   756.2  909.74   769.4  926.51
   805.5  944.67   826.9  960.67   847.5  967.81   874.6  979.88   902.1  995.91
   955.2 1015.15   985.7 1038.94   997.8 1044.89  1012.5  1057.2  1030.2 1064.85
#Mann= 11 ,-1,0
       0      .1       0     210     .06       0     240     .05       0
  456.89     .08       0  556.89      .1       0  649.54    .045       0
   673.5      .1       0  756.47     .06       0  866.47     .05       0
  876.47      .1       0  976.47     .05       0
#XS Ineff= 2 , 0
          565.79  894.48
Permanent Ineff=
       F       F
Bank Sta=649.54,673.5
XS Rating Curve= 0 ,0
Exp/Cntr(USF)=0,0
Exp/Cntr=0.3,0.1

Type RM Length L Ch R = 1 ,21281   ,27.8,26.2,24.4
XS GIS Cut Line= 4
1673569.85861342385012.8095020261673824.32969843385213.889325648
 1673918.2367624385653.5581222221674047.91012074385928.204509117
#Sta/Elev= 30
       0  963.76    23.3  956.72    89.5  943.93   115.3  936.72   176.2  928.21
     217  920.37   251.2  904.24   289.9  896.65     327  894.01   511.1  890.31
   616.2  884.53   662.4  885.27  673.86 882.239   680.3  881.16   710.6  882.18
   723.8  893.18     732  896.72   754.5  899.28   786.1  897.95   789.6  899.34
   821.4  916.08   852.4  935.09   878.9  951.89   909.9  974.36   936.5  989.41
   971.8 1012.96   993.9  1024.7  1012.5 1031.46  1061.1 1060.67  1077.6 1066.93
#Mann= 12 ,-1,0
       0      .1       0     110     .05       0     240     .07       0
  364.33     .08       0  454.33     .05       0  464.33     .08       0
  564.33     .06       0  673.86    .045       0   710.6     .06       0
  764.33     .08       0  853.91     .06       0  873.91     .05       0
#XS Ineff= 2 , 0
          595.65  893.12
Permanent Ineff=
       F       F
Bank Sta=673.86,710.6
XS Rating Curve= 0 ,0
Exp/Cntr(USF)=0,0
Exp/Cntr=0.3,0.1

Type RM Length L Ch R = 1 ,21255   ,48.3,43.3,37.2
XS GIS Cut Line= 5
1673559.96944782385023.8034832351673780.73639075385225.795524863
1673849.36189207385488.6441431351673897.27026092385651.791561372
1674022.86787655385907.518665356
#Sta/Elev= 30
       0  964.58    48.5  950.48   114.1  939.02   179.1  922.57   244.2     909
   267.7  899.43   326.9   892.5   445.2  890.54     484  887.63   508.8  887.81
   554.2  885.57   562.5  885.51   570.9  887.65   591.6  883.93   645.8  884.47
   654.2     882   662.5  881.06   684.7  882.01   695.5  886.34   708.3  894.54
   722.6  897.84   741.8  898.99   765.5  897.75     773  899.68   813.1  921.96
   902.2  982.24   915.6  992.33   977.9 1028.48  1000.2  1036.5  1025.8 1051.74
#Mann= 10 ,-1,0
       0      .1       0     130     .05       0     270     .07       0
  329.23     .08       0  429.23     .05       0  580.89     .06       0
   654.2    .045       0   684.7     .06       0  740.89     .08       0
  840.93     .05       0
#XS Ineff= 2 , 0
          571.47   890.2
Permanent Ineff=
       F       F
Bank Sta=654.2,684.7
XS Rating Curve= 0 ,0
Exp/Cntr(USF)=0,0
Exp/Cntr=0.3,0.1

Type RM Length L Ch R = 1 ,21212   ,44.2,44.9,47
XS GIS Cut Line= 4
1673336.70113881385208.2154679511673617.44247434 385316.83562753
1673884.81517484385656.0647412891674013.48828695385911.739886143
#Sta/Elev= 30
       0 1005.91    33.7  991.06   136.6  938.03   239.6  905.37   284.3  895.06
   302.7  892.45   318.3  887.19   331.2  886.63   342.6   890.2   350.6  890.72
   371.9   886.2   408.1  885.64   434.6  883.52   627.4  884.14   638.8  881.43
   657.2  880.81   668.7881.4214   677.5  883.54     703  883.73   708.1  885.98
   718.3  896.51   723.4  897.88   759.6  897.59   769.3  899.85   791.7  911.89
     841  944.23   903.6   989.9   948.4 1014.59   993.2 1035.17  1019.2 1050.38
#Mann= 7 ,-1,0
       0      .1       0  361.02     .05       0   638.8    .045       0
   668.7     .05       0  681.02     .06       0  721.02     .08       0
  832.95     .05       0
Bank Sta=638.8,668.7
XS Rating Curve= 0 ,0
Exp/Cntr(USF)=0,0
Exp/Cntr=0.3,0.1

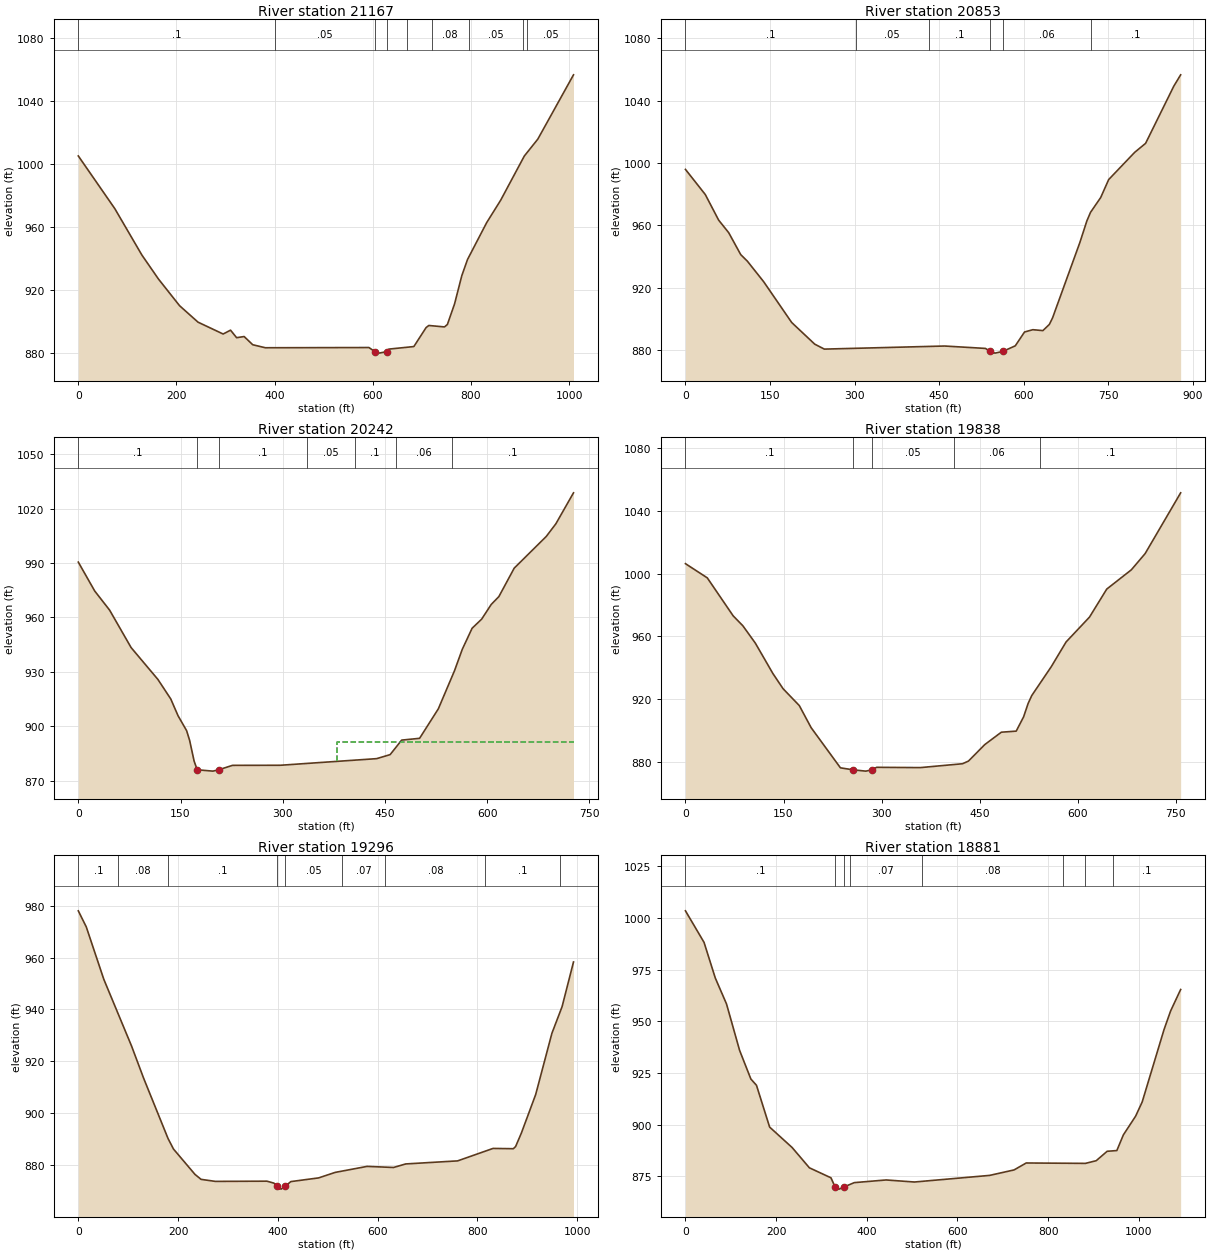
Type RM Length L Ch R = 1 ,21167   ,312.7,313.8,311.4
XS GIS Cut Line= 4
1673309.96386876385259.1833889841673602.40275994385362.790310428
 1673864.7622223385697.0061860541673998.44857255385935.970537126
#Sta/Elev= 30
       0 1005.26    74.4  971.81   129.6  942.35   163.5  927.08   206.4   910.2
     244  899.76   295.1  892.25   310.2  894.69   322.6  889.92   337.9  890.65
   355.4  885.45   381.1  883.53   592.2  883.67   604.5  881.03   612.5  880.12
  628.26881.0165   632.8  882.67   683.7  884.29   708.7  896.35   714.2  897.66
   746.1  896.75     752  898.28   766.7  911.41   781.3  929.16   793.1  939.57
   832.1  962.94   860.7  977.21   908.8 1005.21   936.3 1015.94    1009 1056.74
#Mann= 9 ,-1,0
       0      .1       0  400.25     .05       0   604.5    .045       0
  628.26     .05       0  670.25     .06       0  720.25     .08       0
  795.14     .05       0  905.14      .1       0  915.14     .05       0
Bank Sta=604.5,628.26
XS Rating Curve= 0 ,0
Exp/Cntr(USF)=0,0
Exp/Cntr=0.3,0.1

Type RM Length L Ch R = 1 ,20853   ,613.8,611.2,608.2
XS GIS Cut Line= 4
1673206.07346523385518.4292420611673391.32872368385568.232809175
1673689.11506887385889.0299173941673883.98067134386044.085971951
#Sta/Elev= 30
       0  995.91    35.2  979.76    58.9  963.33    76.7  955.29    98.1  941.18
   109.8     937   138.8  923.78   188.5   897.6   229.4  883.69   246.4  880.52
   459.7   882.5   532.3  880.96  540.64879.0356   549.2  877.94   563.1  879.04
   585.2  882.63   601.6  891.51   616.3  892.98   634.2   892.4   645.6  896.35
   651.3  900.53   699.8  948.99   712.3  962.92   718.7  968.34   736.7  977.81
   750.9  989.37     797 1006.84   816.4 1012.63   866.4 1049.31   878.6 1056.62
#Mann= 6 ,-1,0
       0      .1       0  301.83     .05       0  431.83      .1       0
  540.64    .045       0   563.1     .06       0  719.54      .1       0
Bank Sta=540.64,563.1
XS Rating Curve= 0 ,0
Exp/Cntr(USF)=0,0
Exp/Cntr=0.3,0.1

Type RM Length L Ch R = 1 ,20242   ,403.9,403.6,402.5
XS GIS Cut Line= 4
1673050.09979149385840.0807061581673173.90773912385895.583247349
1673409.66512622386145.1741334861673586.02497091386319.172963188
#Sta/Elev= 30
       0  990.46    24.1  974.54      46  963.98    77.5  943.37   116.9  925.78
   135.7  915.05   146.4  905.81     159  897.56   163.4  892.22     170  880.78
  174.54876.0213   197.5  875.28  206.13876.0225   226.3  878.46   296.6  878.51
   437.9  882.16   457.7  884.38   474.6  892.37   500.9  893.35   528.4   909.6
   552.1  930.55   563.5  942.35     578  954.01     592  959.04   606.1  967.15
   617.3  971.47   639.8  987.14   686.8 1004.59   700.9 1011.56   726.8 1028.64
#Mann= 7 ,-1,0
       0      .1       0  174.54    .045       0  206.13      .1       0
  335.68     .05       0  405.68      .1       0  465.68     .06       0
  549.01      .1       0
#XS Ineff= 2 , 0
                          379.84          891.25
Permanent Ineff=
       F       F
Bank Sta=174.54,206.13
XS Rating Curve= 0 ,0
Exp/Cntr(USF)=0,0
Exp/Cntr=0.3,0.1

Type RM Length L Ch R = 1 ,19838   ,532.9,542.2,541.4
XS GIS Cut Line= 3
1672774.07469488386063.4185512411673120.58971473386399.104976719
1673314.39994916 386593.99368269
#Sta/Elev= 30
       0  1006.3    33.4  997.24      73  972.99    87.8  966.66   106.9  955.58
   133.8  936.15   149.3  926.51   174.1  915.76   192.2  901.66     237  876.04
  256.89874.7218   275.7  873.93  284.99874.7213   292.4  876.36   359.3  876.18
   423.7  878.64   432.8  880.34   457.7  890.85   483.1  898.77   505.8  899.45
   517.1  908.55     524  917.06   529.6  922.15   559.5  940.61   582.1  956.35
   617.9  972.21   644.3  990.09   681.9 1002.38     703 1012.74   757.3  1051.5
#Mann= 5 ,-1,0
       0      .1       0  256.89    .045       0  284.99     .05       0
     410     .06       0  542.45      .1       0
Bank Sta=256.89,284.99
XS Rating Curve= 0 ,0
Exp/Cntr(USF)=0,0
Exp/Cntr=0.3,0.1

Type RM Length L Ch R = 1 ,19296   ,413.7,415.2,411.9
XS GIS Cut Line= 4
1672414.54036895386153.7243555341672419.43822926386351.729876349
1672603.52433355386646.8090729391673042.58469885386730.179371688
#Sta/Elev= 30
       0     978      16   971.8    51.1  951.64   106.8   925.9   130.9  913.55
     180  890.25   190.9  886.22     234  876.45   246.2  874.55   274.9  873.77
   378.2  873.85   392.3  873.09  398.88871.8125   406.5  870.79  414.26871.8116
   426.1  873.69   481.9  875.12   514.9  877.23     579  879.55     632  879.13
   656.4  880.49   760.5  881.67   831.5  886.47   872.2  886.36   876.8  887.21
   888.5  892.49     917  907.24   949.5  930.81   969.9  941.07   992.8  958.29
#Mann= 9 ,-1,0
       0      .1       0      80     .08       0     180      .1       0
  398.88    .045       0  414.26     .05       0  528.07     .07       0
  615.86     .08       0  815.86      .1       0  965.86     .06       0
Bank Sta=398.88,414.26
XS Rating Curve= 0 ,0
Exp/Cntr(USF)=0,0
Exp/Cntr=0.3,0.1

Type RM Length L Ch R = 1 ,18881   ,276.9,262.5,256.5
XS GIS Cut Line= 4
1672238.27749433386092.9106272431672161.57660072 386385.60829023
1672397.42820701386756.7423184891672593.27898147387046.944279556
#Sta/Elev= 30
       0 1003.37      41  988.12    65.8   970.9    90.6  958.33   119.5  935.86
   144.3  922.05   156.7  919.01   185.7  898.81   235.3  888.93   273.4  879.12
     321  874.28  330.28  869.77   339.2  868.81   348.7  869.77   372.4  871.95
   442.7  873.24   505.1  872.25     671  875.45   724.9  878.09   751.7  881.45
   882.4  881.26   906.1  882.55   930.3  887.11   951.6  887.45     966  895.02
     993  904.07  1007.5  910.93  1055.7  945.93  1070.2  954.93  1092.4  965.33
#Mann= 8 ,-1,0
       0      .1       0  330.28    .045       0   348.7      .1       0
  362.58     .07       0  522.58     .08       0  832.32     .06       0
  882.32     .07       0  942.32      .1       0
Bank Sta=330.28,348.7
XS Rating Curve= 0 ,0
Exp/Cntr(USF)=0,0
Exp/Cntr=0.3,0.1

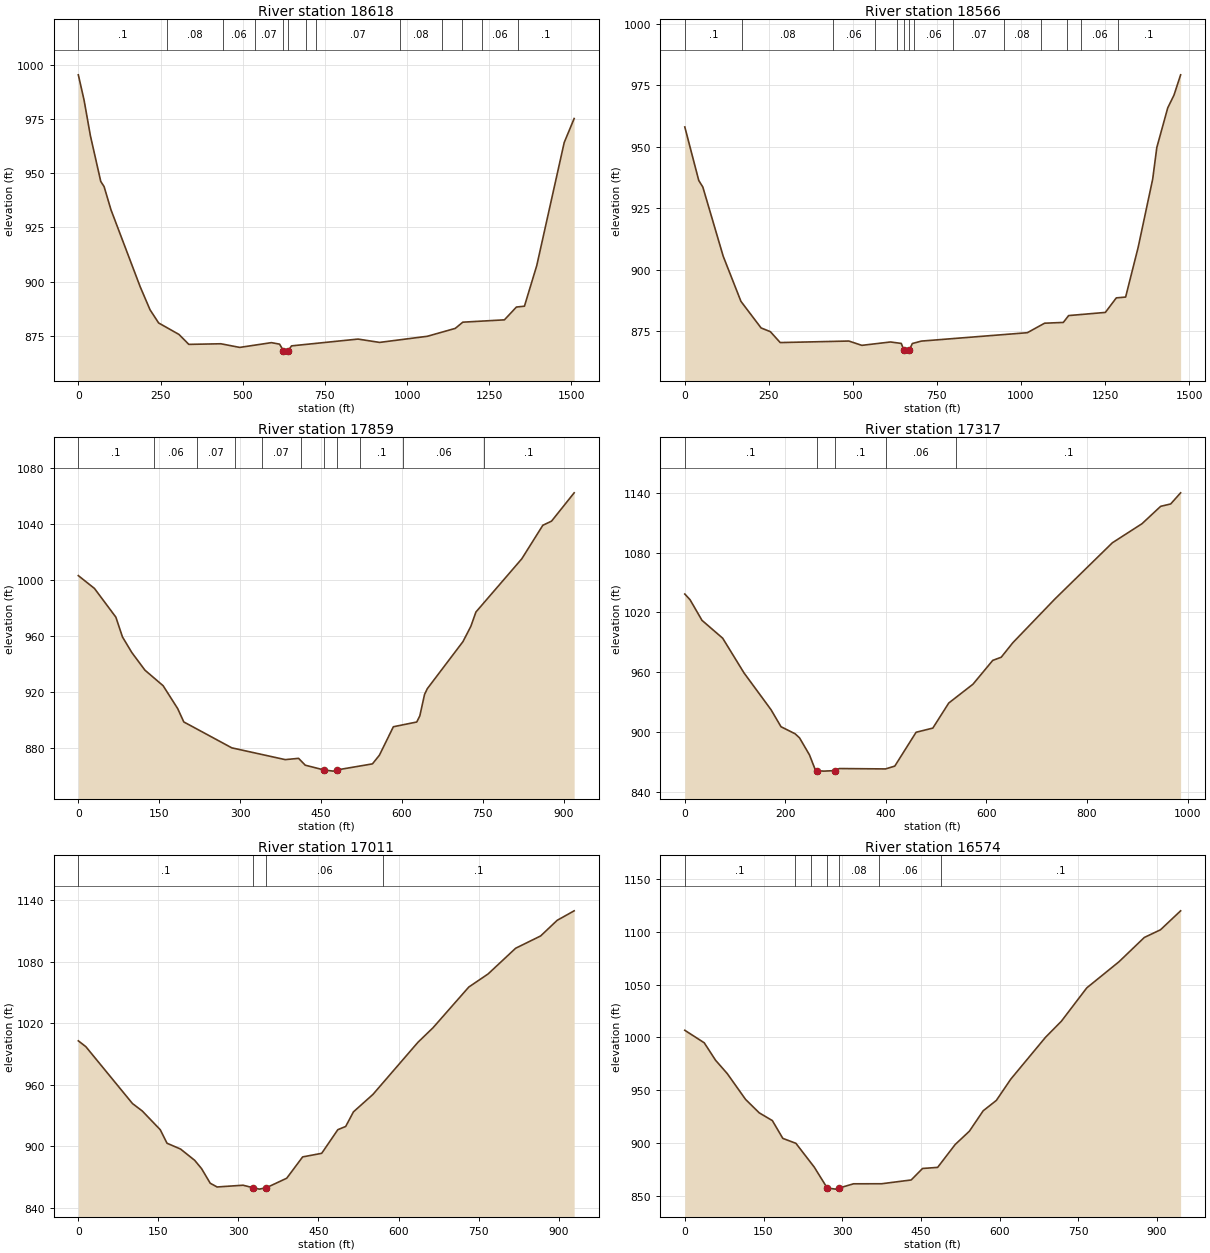
Type RM Length L Ch R = 1 ,18618   ,52.4,52.5,52.5
XS GIS Cut Line= 6
1671538.26634124386366.8553051161671919.82248292386662.840804127
1671940.24678643386636.8462360231672007.08996156 386583.00034495
1672196.53300788386480.1355869931672556.72928064387069.518695824
#Sta/Elev= 30
       0  995.47    17.5  983.76    36.7  967.36    68.2  946.25    78.3  943.87
    99.4  933.11   187.8  897.74   218.1  886.98   244.2   880.9   306.1  875.59
   336.1     871   433.5  871.28   490.9   869.6   587.2   871.8   612.1  871.11
   623.7  868.13   630.3  866.96   638.3868.1481   648.5  870.31   850.6  873.45
   916.3  871.91  1061.6  874.74  1146.4  878.38  1169.4  881.25    1296  882.33
  1332.4  888.23  1356.9  888.64  1394.4  907.42  1477.8  964.19  1508.1  975.29
#Mann= 13 ,-1,0
       0      .1       0     270     .08       0     440     .06       0
  535.96     .07       0   623.7    .045       0   638.3     .07       0
  691.79     .06       0  721.79     .07       0  977.36     .08       0
 1107.36      .1       0 1167.36     .08       0 1227.36     .06       0
 1337.36      .1       0
Bank Sta=623.7,638.3
XS Rating Curve= 0 ,0
Exp/Cntr(USF)=0,0
Exp/Cntr=0.3,0.1

Type RM Length L Ch R = 1 ,18566   ,683.6,706.4,712
XS GIS Cut Line= 6
1671541.78684014386424.4996997921671923.34298181386720.485198804
1672010.61046045386640.6447396261672157.29409475386560.804280449
1672222.28051501 386536.666467211672544.90024701387085.500073661
#Sta/Elev= 30
       0  958.09    41.6  936.32    53.6  933.69   114.3  905.54     167  887.23
   226.9  876.43   254.6   874.9   283.8  870.48   487.9   871.1   526.7  869.35
   611.8  870.72   643.9  870.13  651.94867.3305   658.2  866.19  667.54  867.33
   676.7  870.08   703.7  871.08  1018.9  874.49  1070.2  878.35  1125.9  878.66
  1141.7  881.45  1250.9  882.73  1283.5  888.64  1311.2  888.97  1348.4  909.12
  1391.7  936.89    1404  949.75  1436.5  965.86  1455.1  971.03  1474.8  979.27
#Mann= 14 ,-1,0
       0      .1       0     170     .08       0     440     .06       0
  565.96      .1       0  631.79     .07       0  651.94    .045       0
  667.54     .07       0  681.79     .06       0   798.8     .07       0
  948.12     .08       0 1058.12      .1       0 1138.12     .08       0
 1178.12     .06       0 1288.12      .1       0
Bank Sta=651.94,667.54
XS Rating Curve= 0 ,0
Exp/Cntr(USF)=0,0
Exp/Cntr=0.3,0.1

Type RM Length L Ch R = 1 ,17859   ,547.2,542,533.7
XS GIS Cut Line= 4
1671325.13155525386540.0578575541671588.95524634386759.114575177
1671670.23211938386973.2358041561671861.59813976387263.526485622
#Sta/Elev= 30
       0    1003    29.9  993.84    69.6   973.3    81.9  959.11      99   948.1
   123.5  935.38   157.3  924.22   184.3  907.85   195.6  898.32   284.6  879.78
   383.7  871.35   408.5  872.26   420.9  867.36  455.85  863.94   472.8  863.12
  479.19863.9402   545.5  868.31   558.4  874.52   584.3  894.87   627.7  898.27
   633.4  902.71   642.1  917.95   647.2  922.08   713.4  955.81     728  966.73
   737.4  976.96   822.5 1015.05   861.5 1039.03   877.7    1042   919.6 1062.25
#Mann= 11 ,-1,0
       0      .1       0     140     .06       0     220     .07       0
     290     .08       0     340     .07       0  412.91     .08       0
  455.85    .045       0  479.19     .08       0  522.91      .1       0
  601.94     .06       0  751.94      .1       0
Bank Sta=455.85,479.19
XS Rating Curve= 0 ,0
Exp/Cntr(USF)=0,0
Exp/Cntr=0.3,0.1

Type RM Length L Ch R = 1 ,17317   ,302.9,305.7,306
XS GIS Cut Line= 2
1671013.85194338386888.1541521111671706.00061592387590.767439425
#Sta/Elev= 30
       0 1038.43    10.4 1032.77    34.2 1012.06    75.4  994.12   117.8  959.33
   171.6  922.39   191.4  905.38   219.5  898.28   228.2  894.24     248  877.15
   258.8  863.21   263.5861.3735   276.2  860.85   299.3861.3786   307.3  863.44
   399.2  863.06   417.7  865.87   460.1  899.82   493.4  904.01   525.1  929.16
   573.3  948.04   612.6  971.91   629.4  975.05   652.4  989.54   736.1 1033.41
   850.4 1089.78   909.5 1108.97   946.6 1126.39   966.5 1128.76   986.3 1139.93
#Mann= 5 ,-1,0
       0      .1       0   263.5    .045       0   299.3      .1       0
     400     .06       0     540      .1       0
Bank Sta=263.5,299.3
XS Rating Curve= 0 ,0
Exp/Cntr(USF)=0,0
Exp/Cntr=0.3,0.1

Type RM Length L Ch R = 1 ,17011   ,431.1,438,436.1
XS GIS Cut Line= 4
1670884.61674632387019.2312097091670955.97369737387228.493329754
1671074.62033321387400.614505701 1671335.1995812387826.168307508
#Sta/Elev= 30
       0 1002.88    14.1  997.17   101.5  941.77   119.7   934.6   153.5  916.31
   166.2  903.13   191.6  897.46   218.1  886.46   230.9  878.42   247.1  864.19
     260  860.52   308.6  862.23     328  859.73   339.1  858.43   352.3  859.78
   390.5  869.04   420.3  889.81     456   893.3   486.3  916.35     501  919.47
   515.5  933.68     552  950.65   636.4 1001.46   664.6  1015.6   731.7 1055.28
   767.8    1068   819.4 1093.04   866.3 1105.03   897.2 1120.22   929.1  1129.5
#Mann= 4 ,-1,0
       0      .1       0     328    .045       0   352.3     .06       0
  570.15      .1       0
Bank Sta=328,352.3
XS Rating Curve= 0 ,0
Exp/Cntr(USF)=0,0
Exp/Cntr=0.3,0.1

Type RM Length L Ch R = 1 ,16574   ,163.2,164,163.9
XS GIS Cut Line= 3
 1670479.7160746387226.8222503761670765.47064826387609.499427967
1670957.64477674388035.624669389
#Sta/Elev= 30
       0  1006.8    37.1  994.93    58.7   978.4    80.9  965.84   115.8  941.41
   141.9  928.67   166.9  921.35   186.8  904.53   211.8  899.84   246.8   877.3
  271.45857.5867   287.3  856.52  294.36857.5851   321.6  861.56     375   861.6
   431.5  865.18   453.1  876.05   481.9  877.09   515.2  898.67   542.4  911.32
   568.7  930.64   593.8  940.45   621.3  960.57   687.5 1000.16   717.8  1015.4
   766.1  1046.9   827.6 1071.65   875.8  1094.6   906.6 1101.85     945  1119.8
#Mann= 7 ,-1,0
       0      .1       0     210     .06       0     240     .08       0
  271.45    .045       0  294.36     .08       0     370     .06       0
   487.6      .1       0
Bank Sta=271.45,294.36
XS Rating Curve= 0 ,0
Exp/Cntr(USF)=0,0
Exp/Cntr=0.3,0.1