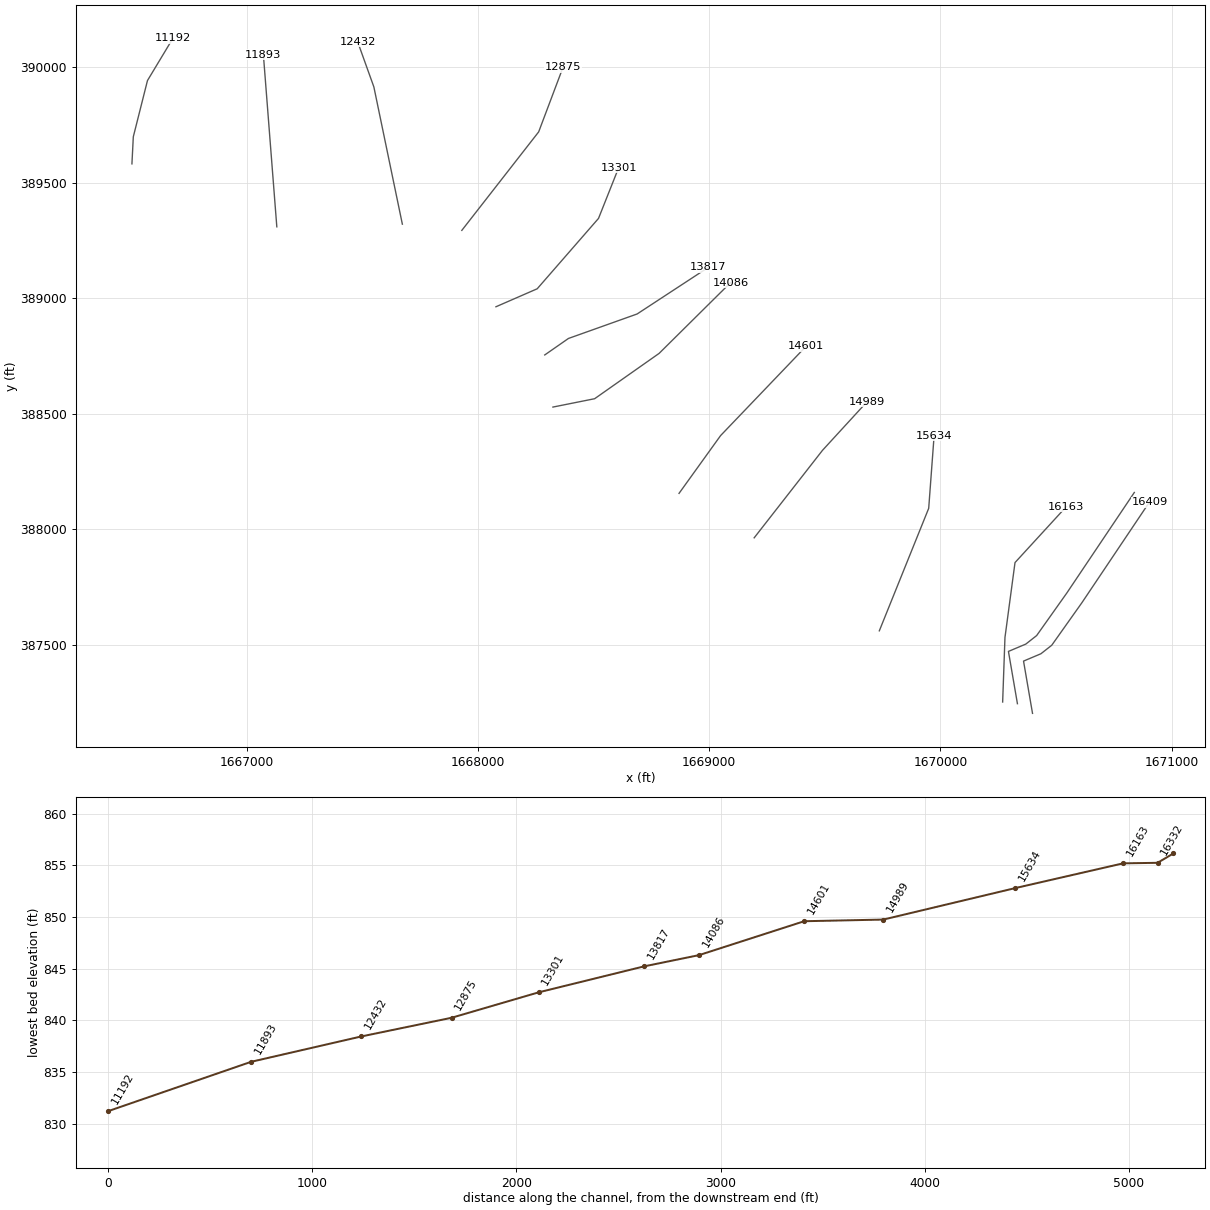
HEC-RAS study NFKFSHNGCK_M.prj: NFKFSHNGCK_M

--- NFKFSHNGCK_M.g01 (geometry) --- (continued)

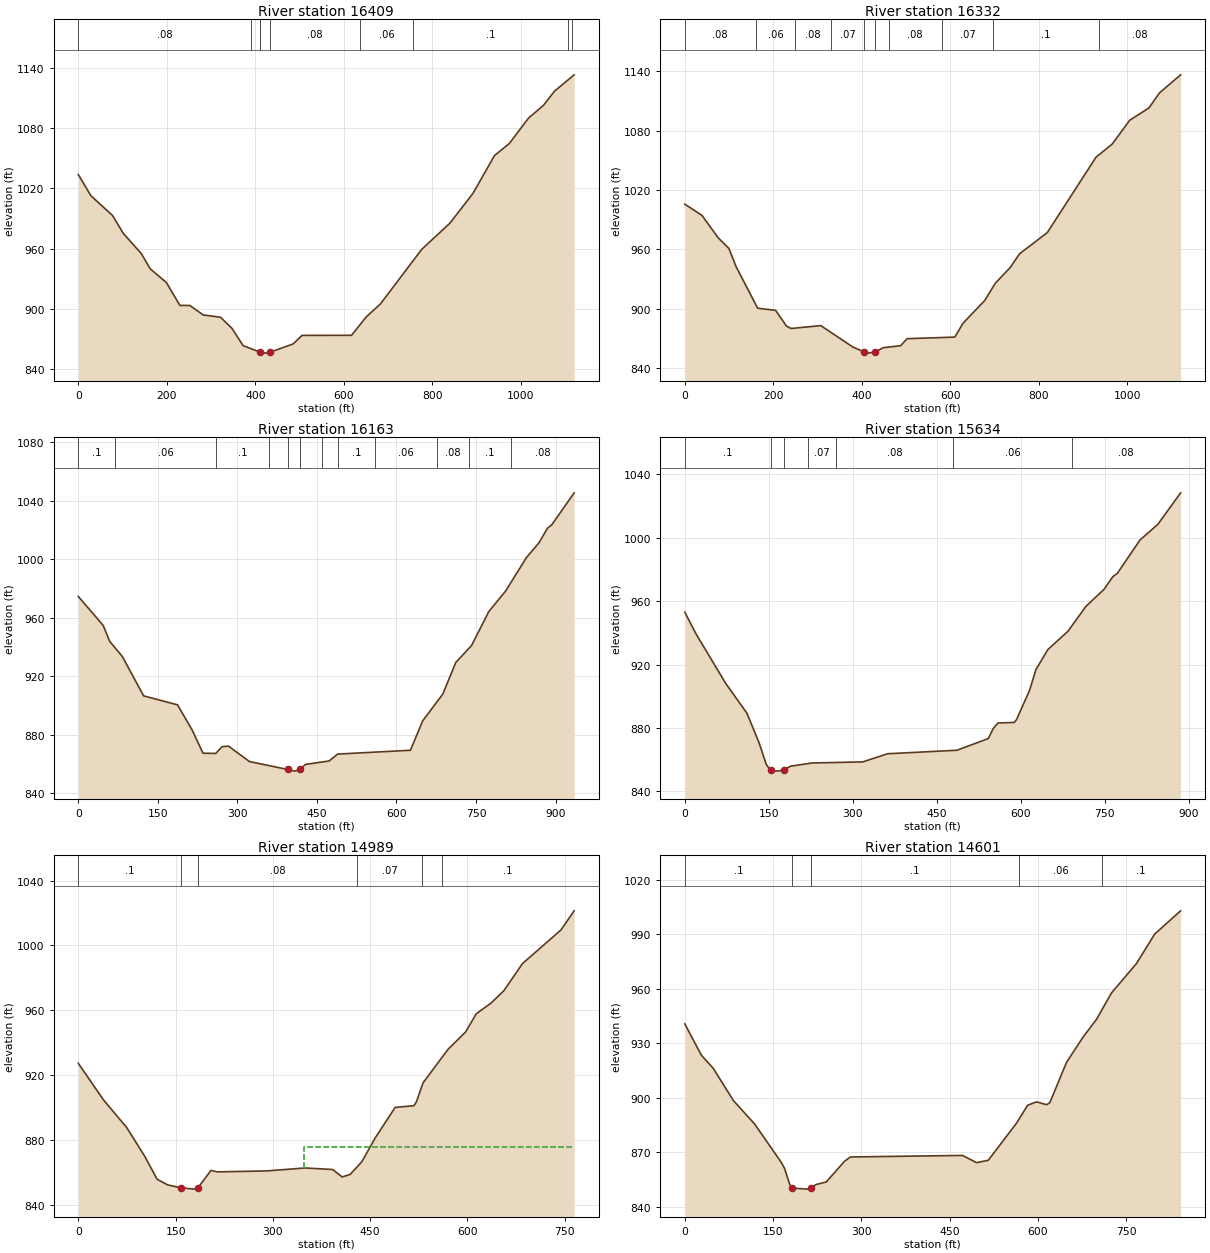
Type RM Length L Ch R = 1 ,16409   ,78,77.7,77.8
XS GIS Cut Line= 6
1670398.39270026387204.4111033321670359.52059845387430.581378841
1670434.71917046387462.3318870251670481.50939305387499.095633344
1670611.85358454387682.9143649381670904.04799757388118.194674046
#Sta/Elev= 30
       0 1033.74    28.5 1012.64    77.2  993.09   101.6  975.21   142.2  955.23
   162.5  939.96     199  926.32   229.5  903.61   251.8  903.54   282.2  894.11
   321.2  891.88   347.1  880.77   372.4  863.57  410.65857.1185   423.5  856.15
   433.8   857.2   485.2  865.28   505.5  873.79   617.2  873.86   650.9  892.35
   682.6   905.1   775.8  959.33   839.5  985.37   891.8 1015.17   940.3 1052.68
   973.7 1064.62  1017.1 1089.87  1050.8 1102.52  1075.8 1116.67  1120.2 1132.91
#Mann= 9 ,-1,0
       0     .08       0  390.62     .07       0  410.62     .08       0
  410.65    .045       0   433.8     .08       0  635.96     .06       0
  755.96      .1       0 1105.96     .08       0 1115.96      .1       0
Bank Sta=410.65,433.8
XS Rating Curve= 0 ,0
Exp/Cntr(USF)=0,0
Exp/Cntr=0.3,0.1

Type RM Length L Ch R = 1 ,16332   ,163.6,168.3,174.8
XS GIS Cut Line= 6
1670333.09836544387246.3006434521670294.22626363387472.470918961
1670369.42483564387504.2214271451670416.21505823387540.985173464
1670546.55924972387724.8039050581670838.75366275388160.084214166
#Sta/Elev= 30
       0  1005.7    38.8  994.35    75.3  971.79    99.7  960.93   115.9  942.57
   164.6  900.59   205.2  898.43   229.5  882.67   240.2  880.12   307.3  883.03
   379.9  861.33  405.24 856.518   414.2  855.24  430.68856.5178   448.5  860.75
   487.8  862.74   502.2  869.83   610.1  871.44   628.6  885.43   677.6  908.39
   701.6  925.86   735.4  941.79   756.6   955.7   818.9  976.89   928.9 1053.01
   965.9 1066.48  1005.1 1090.39  1048.5 1102.81  1072.5 1118.05  1120.2 1136.28
#Mann= 10 ,-1,0
       0     .08       0     160     .06       0  249.49     .08       0
  331.11     .07       0  405.24    .045       0  430.68     .07       0
  460.62     .08       0  580.62     .07       0  695.96      .1       0
  935.96     .08       0
Bank Sta=405.24,430.68
XS Rating Curve= 0 ,0
Exp/Cntr(USF)=0,0
Exp/Cntr=0.3,0.1

Type RM Length L Ch R = 1 ,16163   ,531,529.5,524.6
XS GIS Cut Line= 4
1670269.16007296387253.5595204261670279.18654922387532.629776573
1670322.63461306 387856.819175931670544.88817035388099.125685758
#Sta/Elev= 30
       0  974.57      47  954.75      59     944      83  933.55   123.1  906.66
   187.1   900.5   215.1  883.02   235.1  867.44   259.1  867.28   271.2  871.91
   283.2  872.31   322.7  861.74  395.03856.3209   408.3  855.19  417.79856.3209
   428.5  859.79   472.9  862.11     489  866.84   626.3  869.46   649.4  889.53
   687.4  907.87   711.9   929.5   741.7  941.12   774.2  964.34   805.4  978.09
   845.2 1001.22   868.9 1011.35   884.6 1021.18   893.1 1023.72   935.1 1045.46
#Mann= 12 ,-1,0
       0      .1       0      70     .06       0     260      .1       0
  359.25     .06       0  395.03    .045       0  417.79     .06       0
  459.25     .08       0  489.25      .1       0  559.25     .06       0
  676.34     .08       0  736.34      .1       0  816.34     .08       0
Bank Sta=395.03,417.79
XS Rating Curve= 0 ,0
Exp/Cntr(USF)=0,0
Exp/Cntr=0.3,0.1

Type RM Length L Ch R = 1 ,15634   ,647.2,645.1,641
XS GIS Cut Line= 3
1669735.61865961387561.5714509261669949.24120979388091.512990813
1669972.59587618388405.188712279
#Sta/Elev= 30
       0  952.96    20.4  939.07    73.4  907.94     111  889.33   132.6  870.78
   145.5  857.11  153.18853.2473   162.8  852.79  176.48853.2489   188.6  855.88
   227.5  857.92     318   858.6   362.3  863.74   486.2  865.95   542.3  873.32
   550.9  879.53   559.5  883.13   588.4  883.46   592.5   885.1   616.1  903.79
   627.3  916.74   648.6  929.37   684.7  940.99   716.7  956.64   748.9  967.33
   764.9  975.41     773  977.51   813.1  998.41   845.2 1008.34   885.9 1028.21
#Mann= 7 ,-1,0
       0      .1       0  153.18    .045       0  176.48     .06       0
     220     .07       0     270     .08       0     480     .06       0
  691.38     .08       0
Bank Sta=153.18,176.48
XS Rating Curve= 0 ,0
Exp/Cntr(USF)=0,0
Exp/Cntr=0.3,0.1

Type RM Length L Ch R = 1 ,14989   ,386,387.4,387.3
XS GIS Cut Line= 3
1669194.20992391387963.9218478191669489.88851484388342.563371911
1669681.94021747388551.968654323
#Sta/Elev= 30
       0  927.34    38.8  904.77    74.6  887.72   102.3  870.05   121.5  855.85
   137.8  852.34   158.1  850.59   178.5  849.75  184.42  850.59   204.6   861.3
   213.9  860.39   289.6  860.96   349.5   862.8   392.2  861.85   406.8  857.26
     419  858.79   437.2  866.66   457.5  881.17   488.5  900.14   517.4   901.2
   521.1  903.41   531.5  915.29   569.9   935.9   597.1  946.69   613.6   957.9
   636.3  964.47   656.1  972.13   684.9  988.88   744.1 1009.56   764.5 1021.38
#Mann= 6 ,-1,0
       0      .1       0   158.1    .045       0  184.42     .08       0
     430     .07       0  530.41     .06       0  560.41      .1       0
#XS Ineff= 2 , 0
                          348.39          875.43
Permanent Ineff=
       F       F
Bank Sta=158.1,184.42
XS Rating Curve= 0 ,0
Exp/Cntr(USF)=0,0
Exp/Cntr=0.3,0.1

Type RM Length L Ch R = 1 ,14601   ,518.8,515.1,507.2
XS GIS Cut Line= 3
 1668869.1207802388156.1797894481669048.96039841388406.258728623
1669418.49871879388792.234654752
#Sta/Elev= 30
       0  940.67    28.2  923.39    48.3  916.19    82.6  898.39   118.7  885.47
   162.9  864.83   169.6  860.98   177.8  852.59   182.1850.1708   208.7  849.59
     214850.1718   223.1  852.15   240.3  853.52   271.4  864.97   281.3  867.31
   471.8  868.16   495.8  864.19   515.6  865.49   563.7     886   582.5  895.84
   597.6  897.69   614.6  896.12   620.2  897.24   648.5  919.42   676.8  933.46
   699.5  943.18   724.9  957.69   767.4  973.95   798.4   990.2   842.4 1002.98
#Mann= 5 ,-1,0
       0      .1       0   182.1    .045       0     214      .1       0
  568.03     .06       0  708.03      .1       0
Bank Sta=182.1,214
XS Rating Curve= 0 ,0
Exp/Cntr(USF)=0,0
Exp/Cntr=0.3,0.1

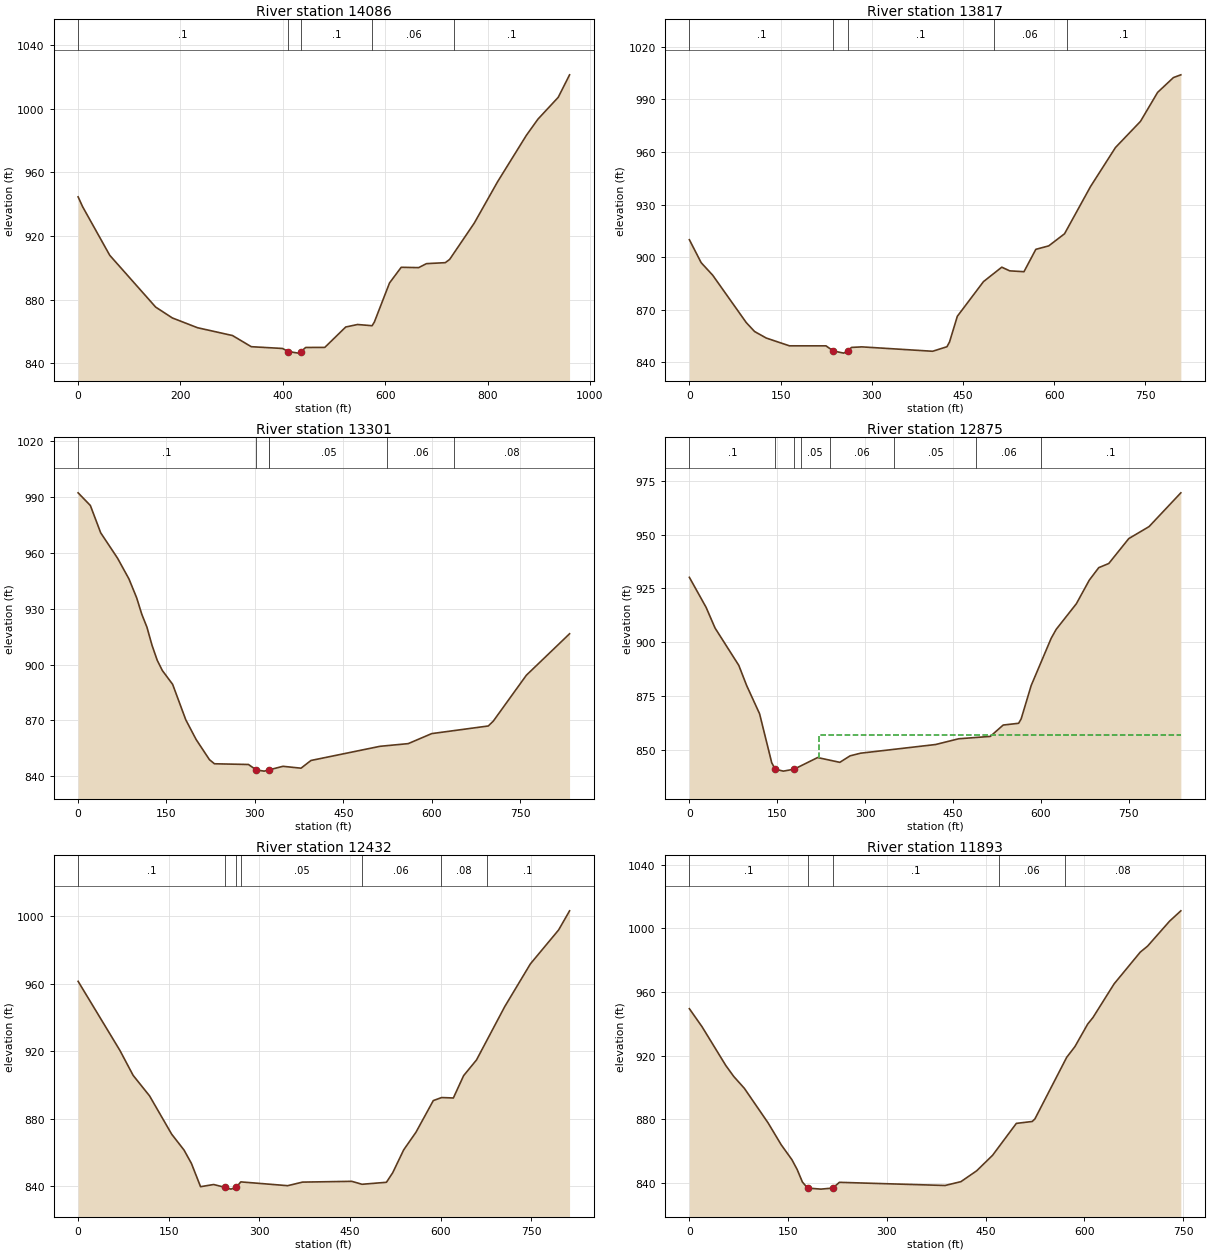
Type RM Length L Ch R = 1 ,14086   ,269.8,269.5,263.5
XS GIS Cut Line= 4
1668323.53040715388529.5731507251668503.95122787 388565.69474101
1668782.92289033388761.8276565421669092.03739991389067.983572567
#Sta/Elev= 30
       0   944.6     8.8  938.39    61.8  907.84   151.5  875.26     184  868.45
   233.1   862.3   301.6  857.37   338.3  850.35   399.3  849.24  410.54847.3314
   430.2  846.31  435.53847.3336   444.6  849.87   481.9  849.91   522.8  862.74
   545.9  864.31   574.3  863.55   578.7  865.83   608.4  890.46   631.2  900.29
   665.3  900.08   680.5  902.58   717.3   903.2   725.8  905.24   773.9  928.08
   819.4  954.05   875.7  983.28   898.3  993.45   937.9 1007.17   960.1 1021.33
#Mann= 5 ,-1,0
       0      .1       0  410.54    .045       0  435.53      .1       0
  575.02     .06       0  735.02      .1       0
Bank Sta=410.54,435.53
XS Rating Curve= 0 ,0
Exp/Cntr(USF)=0,0
Exp/Cntr=0.3,0.1

Type RM Length L Ch R = 1 ,13817   ,510.1,515.8,515.3
XS GIS Cut Line= 4
1668288.15412325388755.0594228231668390.65705927388826.393150474
1668687.90197474388932.3780178731668995.62905195389133.839779824
#Sta/Elev= 30
       0  909.95    19.4  896.85    38.4  889.68    93.6  862.63   107.2  857.56
   126.4  853.83   164.6  849.39   224.7  849.37  236.65  846.46   253.8  845.22
  260.33846.4637   266.6  848.47   283.6  848.79   400.1  846.28   423.7  848.88
   427.9  851.62   440.7  866.25   483.7  886.04   513.8  894.28   526.8  892.19
   550.3   891.7   569.8  904.46     591  906.44     617  913.34   659.8  940.33
   700.8  962.59   741.9   977.5   770.1  994.06   796.1 1002.51   808.3 1004.08
#Mann= 5 ,-1,0
       0      .1       0  236.65    .045       0  260.33      .1       0
  500.46     .06       0  620.46      .1       0
Bank Sta=236.65,260.33
XS Rating Curve= 0 ,0
Exp/Cntr(USF)=0,0
Exp/Cntr=0.3,0.1

Type RM Length L Ch R = 1 ,13301   ,423.4,426.3,426
XS GIS Cut Line= 4
 1668077.0235778388963.5588170181668255.53852293  389041.3379017
  1668520.839085389345.8921183631668607.77133667389564.734983501
#Sta/Elev= 30
       0  992.25    20.8  985.44    38.3  970.78    66.9  957.15    86.3  945.98
    99.4  935.82   108.1  926.99   116.8  920.07   125.5  910.27   134.3  902.25
     143  896.75   160.4  889.36   182.7  870.32   200.2  859.75   222.9  848.87
   231.4  846.66   289.1  846.28  302.51843.3445   315.7  842.71  323.73843.3445
   347.7   845.3   378.3  844.29   395.2  848.43   512.3  856.04   560.3  857.49
   600.1  862.87   696.2  866.97   704.8  869.65   760.7  894.22   834.1  916.52
#Mann= 6 ,-1,0
       0      .1       0  302.51    .045       0  323.73      .1       0
  324.72     .05       0  524.72     .06       0  638.63     .08       0
Bank Sta=302.51,323.73
XS Rating Curve= 0 ,0
Exp/Cntr(USF)=0,0
Exp/Cntr=0.3,0.1

Type RM Length L Ch R = 1 ,12875   ,430.8,442.7,451
XS GIS Cut Line= 3
1667929.37468291389293.9808727181668261.90801734389720.211836003
1668367.27747485389999.673684298
#Sta/Elev= 30
       0  930.17    28.6  916.22    43.8  906.67    84.4  889.32    97.8  879.97
   119.9  866.86   140.6  844.17  146.46 841.142   160.5  840.25  178.81841.1425
     219  846.55   256.9  844.33   274.5  847.35   292.4  848.57   420.6   852.6
   459.8  855.26   513.9  856.36   535.9  861.63   562.3  862.45   566.6  864.49
   583.7  879.96   617.9  901.91   626.4  906.02   660.9  917.93   682.9  928.84
   699.1  934.66   716.2  936.58   750.4  948.15     785   953.7   839.3  969.38
#Mann= 8 ,-1,0
       0      .1       0  146.46    .045       0  178.81      .1       0
     190     .05       0     240     .06       0     350     .05       0
     490     .06       0   600.6      .1       0
#XS Ineff= 2 , 0
                          221.41          857.06
Permanent Ineff=
       F       F
Bank Sta=146.46,178.81
XS Rating Curve= 0 ,0
Exp/Cntr(USF)=0,0
Exp/Cntr=0.3,0.1

Type RM Length L Ch R = 1 ,12432   ,538.3,538.8,536.7
XS GIS Cut Line= 3
1667672.12840602389320.8247456791667548.86815024389914.591162323
1667478.84065684390109.555013633
#Sta/Elev= 30
       0  961.54    69.2  920.61    91.1  905.82   118.2  893.72   154.9  870.99
   175.4  861.56   187.6  853.65   202.7  839.89   224.4  841.17  243.62839.4352
     253  838.44  261.71839.4385   269.3  842.73     347  840.48   371.5   842.6
   453.1  843.06     470  841.31   510.4  842.49   520.8  848.15     539  861.71
   559.4   872.2     588   890.9   601.9   892.7   621.2  892.43   638.2  905.67
   659.5  914.96   706.2  946.52   748.7  971.86   795.5     992   813.6 1003.31
#Mann= 7 ,-1,0
       0      .1       0  243.62    .045       0  261.71      .1       0
     270     .05       0     470     .06       0     600     .08       0
  676.43      .1       0
Bank Sta=243.62,261.71
XS Rating Curve= 0 ,0
Exp/Cntr(USF)=0,0
Exp/Cntr=0.3,0.1

Type RM Length L Ch R = 1 ,11893   ,709.2,701.2,689.2
XS GIS Cut Line= 2
1667129.01351059389309.3218893051667070.90266244390053.667627505
#Sta/Elev= 30
       0  949.51    19.3  938.12    55.4  913.73    67.4  906.87    83.5  899.42
   119.6  877.65   139.6  863.83   155.7  854.56   163.7  848.35   171.7  840.47
  179.58 836.658   199.8  835.99  217.82 836.658   227.9  840.27   388.4  838.28
   412.5  840.69   436.5  847.54   460.6  857.28   496.7  877.35   520.8  878.55
   524.9  880.16   573.2  918.92   585.7  925.66   605.1  939.85   613.1  943.96
   645.2  965.12   684.9  985.08   696.1   988.9   729.5 1004.59   746.6 1011.09
#Mann= 5 ,-1,0
       0      .1       0  179.58    .045       0  217.82      .1       0
     470     .06       0     570     .08       0
Bank Sta=179.58,217.82
XS Rating Curve= 0 ,0
Exp/Cntr(USF)=0,0
Exp/Cntr=0.3,0.1

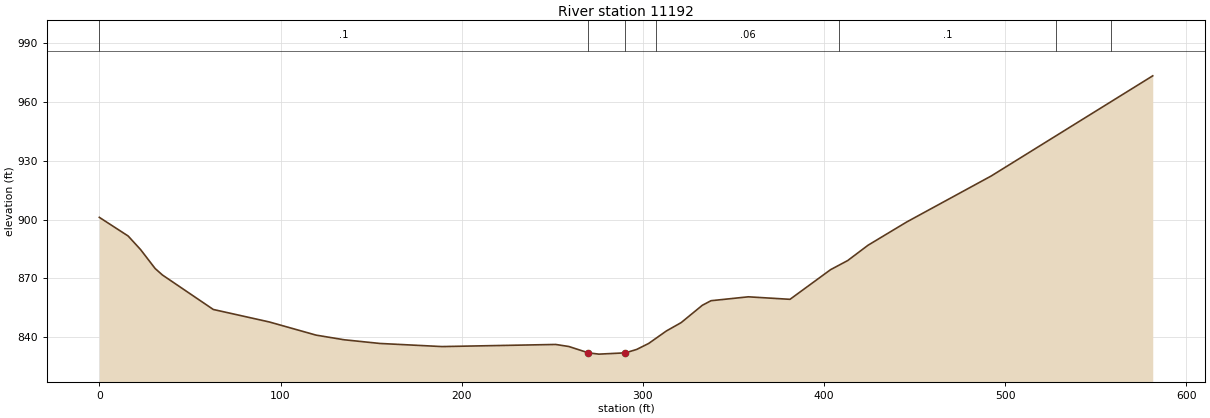
Type RM Length L Ch R = 1 ,11192   ,639.9,627.2,613.2
XS GIS Cut Line= 4
1666502.19659954389581.742405345 1666508.1586653389699.001847088
1666569.43157583389942.2367343481666679.44059444  390124.8294202
#Sta/Elev= 30
       0  901.11    15.9  891.58    22.8   884.6    30.8  874.96    34.8  871.67
    62.9  854.03    93.8  847.65   119.6  840.93   135.1  838.55   154.9  836.66
   189.1  835.07   251.9  836.15   259.2  835.09  269.94831.8588   275.7  831.21
  290.35831.8588   296.6  833.62   303.2  836.67     313  843.07   321.1   847.3
   332.8  856.17   337.6  858.51   358.2   860.5   381.2  859.22   403.6  874.38
     413  879.01   424.3  886.88   445.6  898.74   492.3  922.28   581.4  973.44
#Mann= 7 ,-1,0
       0      .1       0  269.94    .045       0  290.35      .1       0
  307.41     .06       0  408.24      .1       0  528.24     .08       0
  558.24      .1       0
Bank Sta=269.94,290.35
XS Rating Curve= 0 ,0
Exp/Cntr(USF)=0,0
Exp/Cntr=0.3,0.1