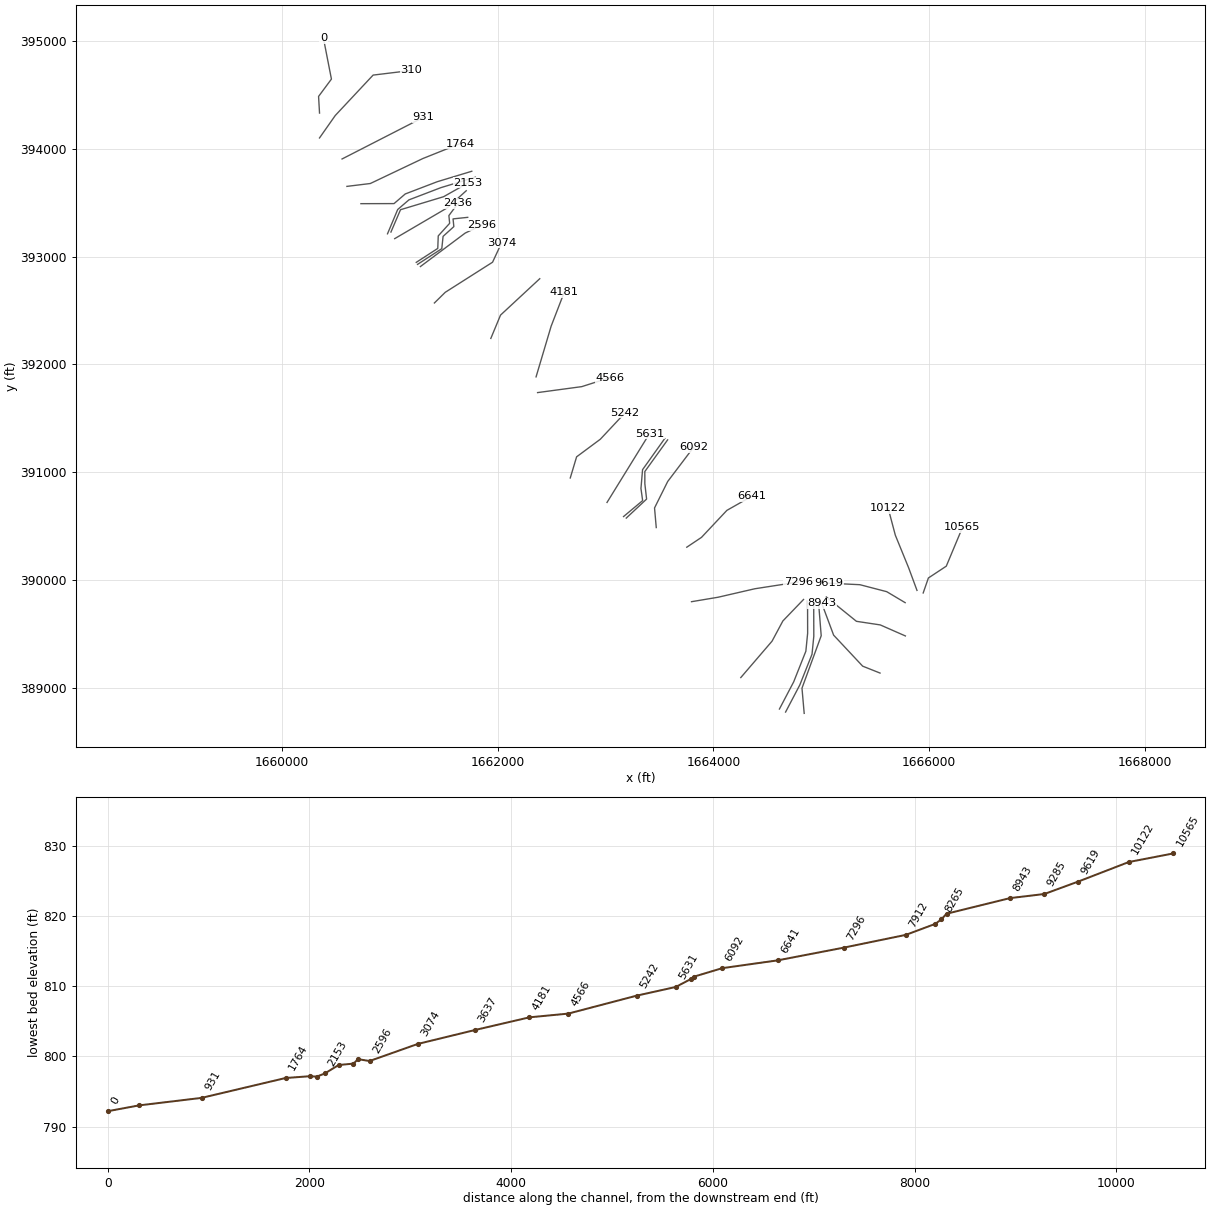
HEC-RAS study NFKFSHNGCK_M.prj: NFKFSHNGCK_M

--- NFKFSHNGCK_M.g01 (geometry) --- (continued)

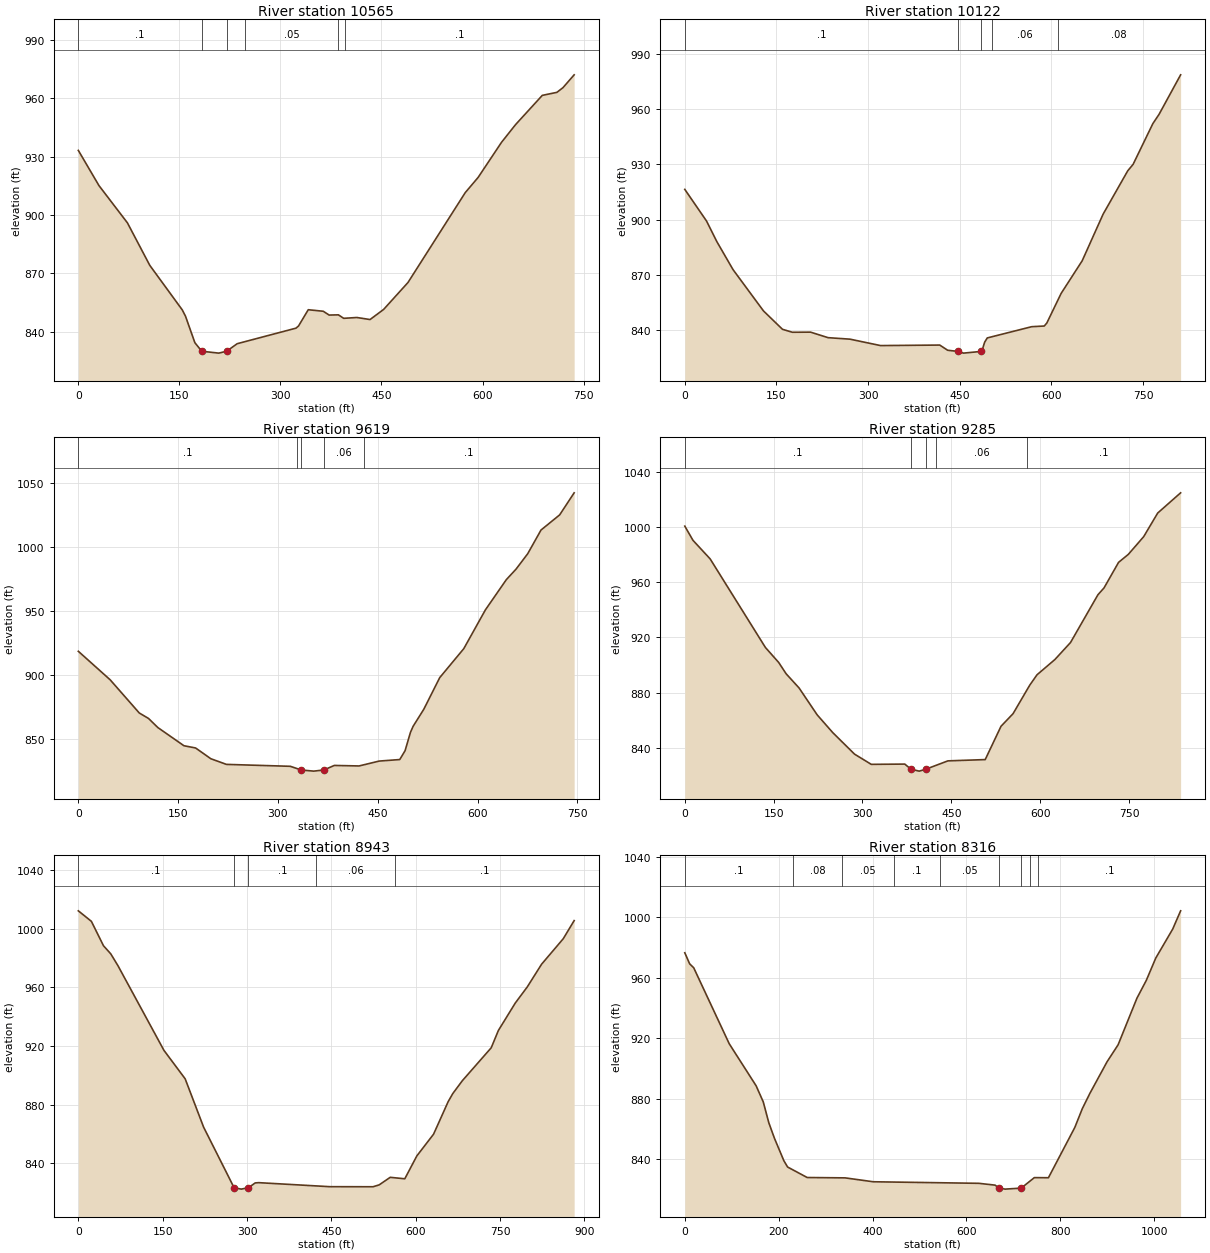
Type RM Length L Ch R = 1 ,10565   ,421.5,443,472
XS GIS Cut Line= 4
1665945.95600579389879.6542865391665994.18027088390018.736819438
1666160.04832167390128.3153222871666310.49184937390488.173779779
#Sta/Elev= 30
       0  933.21    30.6  915.12    72.9  895.92   106.1  874.05   154.3  851.14
   159.1  847.88     173  834.26  183.23829.8756   208.5   828.9   220.2829.8754
   235.8  833.75   323.1  841.75   326.9  842.88   341.3  851.23   363.6  850.44
   372.3  848.48     386   848.6   393.9  846.81   413.5  847.23     433  846.18
   453.2  851.39   489.3  865.22   574.3  911.47   593.4  919.28     628  937.29
   648.9  946.43   688.7  961.53   710.4  963.08   719.5  965.53     736   972.1
#Mann= 6 ,-1,0
       0      .1       0  183.23    .045       0   220.2      .1       0
  247.21     .05       0     386     .06       0     396      .1       0
Bank Sta=183.23,220.2
XS Rating Curve= 0 ,0
Exp/Cntr(USF)=0,0
Exp/Cntr=0.3,0.1

Type RM Length L Ch R = 1 ,10122   ,486.6,502.8,520
XS GIS Cut Line= 4
1665888.44739667389903.4090165721665811.07449765390112.867400088
1665687.59073341 390415.718137241665620.62984003  390668.2278864
#Sta/Elev= 30
       0   916.4    35.6  899.24    52.4  888.12      79   872.9   128.8  850.54
   159.9  840.58     176  838.98   205.9  839.04   234.5  836.05   270.5  835.23
   320.4  831.76   417.3  832.04   430.3  829.22   447.6  828.58   456.2  827.67
  485.18828.5986   486.4  828.85   490.8  833.58   495.1   835.9   567.8  841.99
   588.4  842.36   592.6  843.99     616  860.02   650.5  877.72   684.7  902.95
     725  926.44   733.8  929.95   766.2  952.06   776.3  957.06   811.6  978.47
#Mann= 5 ,-1,0
       0      .1       0   447.6    .045       0  485.18      .1       0
  503.29     .06       0  610.35     .08       0
Bank Sta=447.6,485.18
XS Rating Curve= 0 ,0
Exp/Cntr(USF)=0,0
Exp/Cntr=0.3,0.1

Type RM Length L Ch R = 1 ,9619    ,331,333.6,334.8
XS GIS Cut Line= 4
1665778.74897615389789.6277282581665607.75105021389891.606657657
1665359.00033461389956.2751855461665070.32771224389970.394105282
#Sta/Elev= 30
       0  918.49    47.8  896.24    91.6  870.29   105.5  866.02   119.5  858.92
   158.7  844.72   176.2  842.97   199.1  834.57   222.5  830.15   318.6  828.64
   335.1  825.75   353.7  824.88  368.86 825.765   384.7  829.32   421.9  828.92
   452.1  832.73     483  833.92     491  840.82   499.1  855.15   503.1  859.89
   519.1  873.16   543.1  897.92   579.2  920.52   611.8   950.9   643.2  974.47
   657.7  982.62   675.3  994.69   695.3 1013.21   723.3 1025.03   745.1 1042.27
#Mann= 5 ,-1,0
       0      .1       0   329.1     .06       0   335.1    .045       0
  368.86     .06       0   429.1      .1       0
Bank Sta=335.1,368.86
XS Rating Curve= 0 ,0
Exp/Cntr(USF)=0,0
Exp/Cntr=0.3,0.1

Type RM Length L Ch R = 1 ,9285    ,348.4,342.2,331.3
XS GIS Cut Line= 4
  1665780.736275389480.7692706421665547.92728908389583.073164668
1665326.97346019389616.4947522311665047.57743053389842.429205507
#Sta/Elev= 30
       0 1000.62    13.8  990.35    42.8  976.88   136.1  912.71   158.5  901.86
   171.1  893.64   192.9  883.39   223.5  863.89   249.7  851.07   286.5  835.46
   314.8  828.03   371.4  828.22   381.9  824.49   395.7  823.12  406.44824.4272
   444.2  830.55   507.2  831.48   533.9  855.63   554.2  864.74   582.2  885.27
   594.6   892.9   624.9     904   651.2  916.29   697.5  950.91   707.8  955.87
   732.3  974.35   748.9   980.2   774.7  992.97   798.4  1010.1   837.1 1024.75
#Mann= 5 ,-1,0
       0      .1       0   381.9    .045       0  406.44      .1       0
   424.3     .06       0  577.76      .1       0
Bank Sta=381.9,406.44
XS Rating Curve= 0 ,0
Exp/Cntr(USF)=0,0
Exp/Cntr=0.3,0.1

Type RM Length L Ch R = 1 ,8943    ,634,627.4,606.4
XS GIS Cut Line= 4
1665545.68826279389136.3425762381665384.59654439389200.426817224
1665115.36708902389488.2238212351665005.58049039 389782.74919746
#Sta/Elev= 30
       0 1012.04    23.2 1004.89    44.7  988.29    57.7  982.73    70.6  974.59
   152.3  917.01     190  897.65   222.8  864.74  276.98823.5272   289.8  822.53
  302.62823.5276   314.6  826.76   320.9  826.93   447.4  824.19   524.1  824.15
     535  825.42   554.7  830.57   580.6  829.57     602  845.13   631.8  859.96
   657.7  882.07     666  887.63   683.1  896.43   734.3  918.78   747.1   930.6
     777   949.2   798.3  960.15   823.9  975.69   862.4  993.04   881.8 1005.37
#Mann= 5 ,-1,0
       0      .1       0  276.98    .045       0  302.62      .1       0
  423.37     .06       0  563.37      .1       0
Bank Sta=276.98,302.62
XS Rating Curve= 0 ,0
Exp/Cntr(USF)=0,0
Exp/Cntr=0.3,0.1

Type RM Length L Ch R = 1 ,8316    ,47.2,51,60.5
XS GIS Cut Line= 4
1664842.42412393388762.2326691831664821.99982042 388996.18378212
1665000.24828742389482.6535566411664976.11047418389785.304599568
#Sta/Elev= 30
       0   976.6    10.3  969.32      19  966.68    94.7  916.44     152  888.65
   167.2  878.02     179  864.24     191  853.98   211.1   839.1   219.1  834.93
   260.8  827.99   341.7  827.75   401.4  825.18   626.5  824.15   661.2  822.95
   669.7  821.03   682.5  820.31   716.9  820.98   744.9  827.92   774.9  827.84
   831.1  861.08   847.1  873.53   863.2  883.61   899.7  904.45   923.4  915.76
   963.5  946.57   983.6  958.43  1003.6  973.09  1039.7  992.26  1056.6 1004.34
#Mann= 9 ,-1,0
       0      .1       0     230     .08       0  334.84     .05       0
  444.84      .1       0  544.84     .05       0   669.7    .045       0
   716.9     .05       0  734.84     .06       0  752.94      .1       0
Bank Sta=669.7,716.9
XS Rating Curve= 0 ,0
Exp/Cntr(USF)=0,0
Exp/Cntr=0.3,0.1

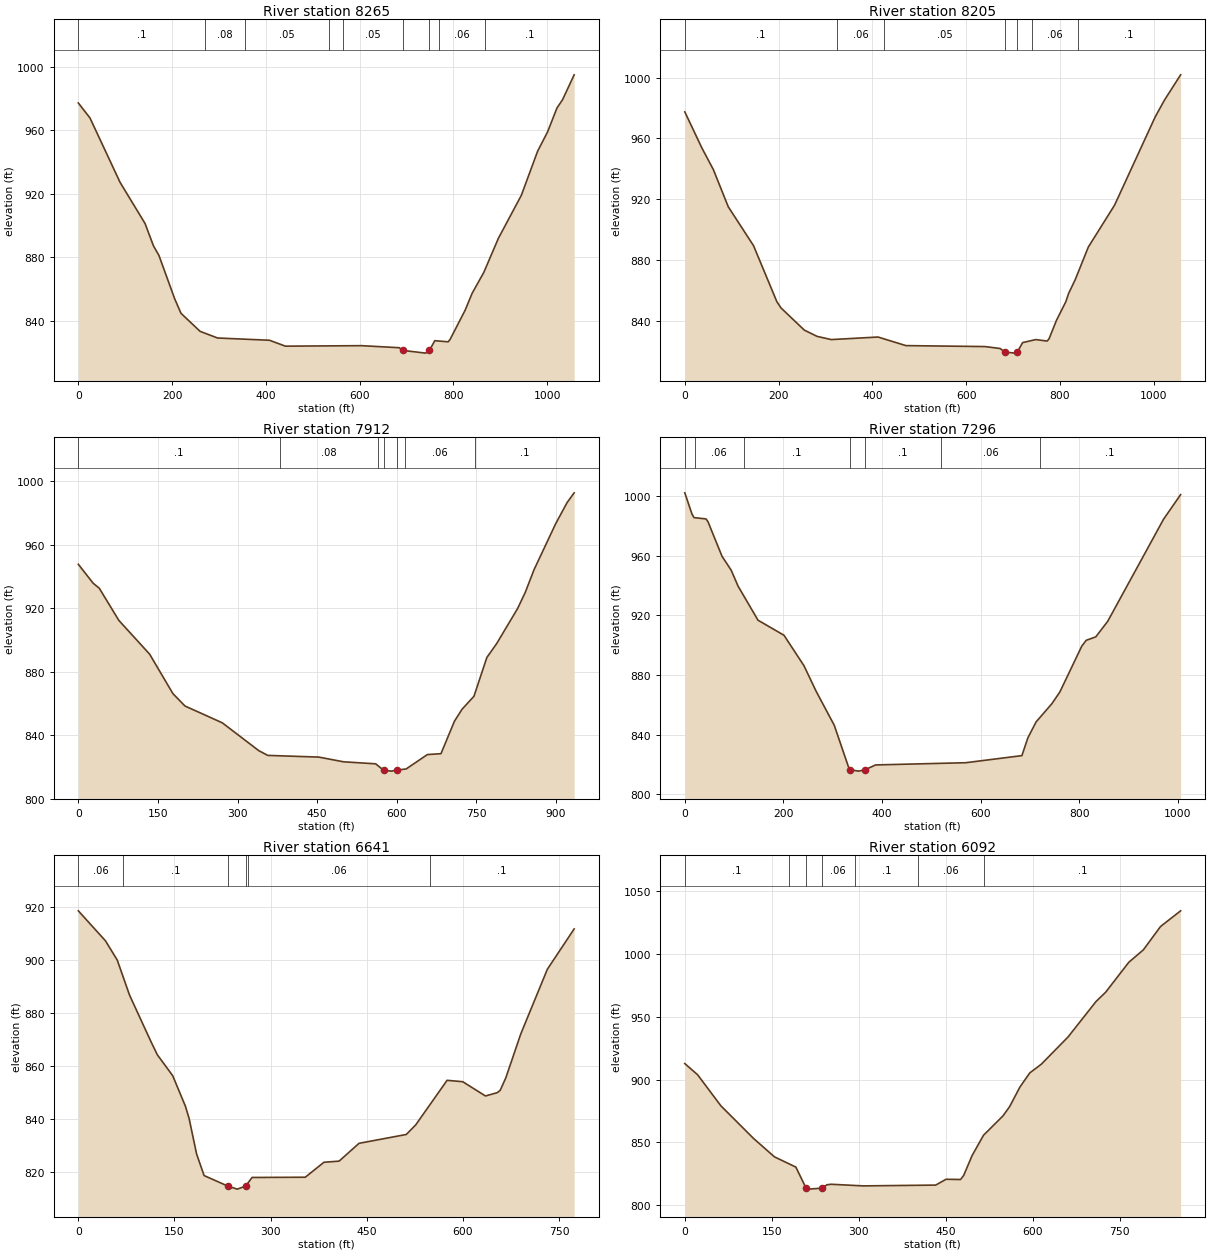
Type RM Length L Ch R = 1 ,8265    ,61.1,59.8,62.4
XS GIS Cut Line= 5
1664669.95239857388774.546339139 1664802.2231471389026.760542957
1664915.02100512389311.0111451771664931.56469097389477.951975051
 1664930.7814218389777.261465801
#Sta/Elev= 30
       0  977.13    24.8  967.72      89  927.15   142.3  901.22   160.3   887.1
     172  881.06   205.5  853.78     219  844.62   259.7  833.26   296.9  829.06
   407.8  827.63   441.7  823.91   604.2  824.22   684.6  822.93  692.26821.2384
   740.9  819.52   748.9  821.19   760.4  827.35     789  826.65     793  828.13
     825  846.48   840.2  857.29     865   870.4     896  891.83     945  918.94
   979.8  946.77    1001  958.92    1021  973.94    1033  979.24  1057.7  994.88
#Mann= 9 ,-1,0
       0      .1       0     270     .08       0  354.79     .05       0
  534.79      .1       0  564.79     .05       0  692.26    .045       0
   748.9     .05       0  768.37     .06       0  868.37      .1       0
Bank Sta=692.26,748.9
XS Rating Curve= 0 ,0
Exp/Cntr(USF)=0,0
Exp/Cntr=0.3,0.1

Type RM Length L Ch R = 1 ,8205    ,295.9,292.9,285.6
XS GIS Cut Line= 5
1664612.84085295388802.6058969251664745.11160148389054.820100744
 1664857.9094595389339.0707029631664874.45314535389506.011532837
1664873.66987618389805.321023587
#Sta/Elev= 30
       0  977.44    36.4  953.73    60.9   939.5    92.7  915.07   146.7  889.44
   196.4  852.67   205.4  848.52   255.1  833.97   282.2  829.88   312.5  827.77
   412.2  829.45   471.7  823.81   640.3  823.18   672.5  821.92  683.17819.5675
   704.6  818.87  709.28819.5681   720.7   825.8   748.8  827.78   772.9  826.79
   776.9  828.22   792.9  840.44   812.9  852.71   818.7  858.05   832.9  867.18
   860.9  888.62   916.9  916.16  1003.2  973.94  1023.2  985.14  1057.7 1001.76
#Mann= 7 ,-1,0
       0      .1       0  324.79     .06       0  424.79     .05       0
  683.17    .045       0  709.28     .05       0  740.61     .06       0
  838.37      .1       0
Bank Sta=683.17,709.28
XS Rating Curve= 0 ,0
Exp/Cntr(USF)=0,0
Exp/Cntr=0.3,0.1

Type RM Length L Ch R = 1 ,7912    ,626.2,616.4,600.2
XS GIS Cut Line= 4
1664254.75093995389094.5895966021664544.44561693389432.403287053
1664644.70394107389619.7058687271664836.31798277389819.126151533
#Sta/Elev= 30
       0  947.76    27.9  935.82    39.5  932.64    76.3  912.38   134.3  891.08
   178.2  866.17   200.9  858.37   271.3  847.75   339.8  830.24   356.9  827.22
   452.8  826.16   499.6  823.18   560.1  821.91   574.9   817.9   589.7   817.3
   599.4  817.88   617.6  818.68   657.6  827.75   683.1   828.3   708.5  848.77
   722.7  856.28   745.3  864.55   769.6  889.01   787.8  897.61   827.4  919.82
   841.7  929.88   858.5  944.39   899.1  973.29   920.7  986.68     934  992.83
#Mann= 7 ,-1,0
       0      .1       0     380     .08       0  565.02      .1       0
   574.9    .045       0   599.4      .1       0  615.02     .06       0
  747.47      .1       0
Bank Sta=574.9,599.4
XS Rating Curve= 0 ,0
Exp/Cntr(USF)=0,0
Exp/Cntr=0.3,0.1

Type RM Length L Ch R = 1 ,7296    ,641.4,654.7,658.2
XS GIS Cut Line= 4
1663797.68419581389798.6199157181664044.73275878389840.133583656
1664384.93829285389918.7124365881664786.31020949389980.918718861
#Sta/Elev= 30
       0 1002.04    14.6  987.81    18.7  985.43      43  984.54    47.1  982.63
    75.5  959.51    94.1  950.18     108  939.53   148.5  916.66   201.2  906.56
   241.8  886.13   266.3  869.09   303.2  846.21     332  818.33  335.97816.3528
   352.5  815.48  365.42816.3544   387.1  819.63   570.1  821.12   683.8  825.88
     696  837.81   712.7  848.51   744.6  860.67   760.8  868.52   805.3  899.26
   814.3  903.19   833.6  905.45   857.9   915.9   971.2  984.36  1005.8 1000.82
#Mann= 7 ,-1,0
       0      .1       0      20     .06       0     120      .1       0
  335.97    .045       0  365.42      .1       0  520.51     .06       0
  719.67      .1       0
Bank Sta=335.97,365.42
XS Rating Curve= 0 ,0
Exp/Cntr(USF)=0,0
Exp/Cntr=0.3,0.1

Type RM Length L Ch R = 1 ,6641    ,542.4,549.2,551
XS GIS Cut Line= 4
1663753.67689389390304.2898022891663890.36617627 390395.70280728
1664125.47536807390646.0218845941664356.43913817390777.234103817
#Sta/Elev= 30
       0  918.73    42.3  907.42    60.7  900.15    79.9  886.91   113.6   869.2
   123.2  864.41   147.3  856.46     167     845   172.8  840.36   184.5  826.93
   196.2  818.79  233.37814.8015   247.9  813.67  261.05 814.804     271  818.07
     354  818.16   383.2  823.81   406.8  824.24   437.9  830.96   511.6   834.3
   526.3  837.91   575.3  854.75   599.7  854.22   635.1  848.84   653.5  850.08
   658.1  850.96   666.8  855.63   690.3   872.3   731.7  896.68   773.5   911.9
#Mann= 6 ,-1,0
       0     .06       0      70      .1       0  233.37    .045       0
  261.05      .1       0  264.44     .06       0  547.86      .1       0
Bank Sta=233.37,261.05
XS Rating Curve= 0 ,0
Exp/Cntr(USF)=0,0
Exp/Cntr=0.3,0.1

Type RM Length L Ch R = 1 ,6092    ,277.6,282.5,292.2
XS GIS Cut Line= 4
1663470.59796798390486.5250445931663454.70410569390668.581456199
1663576.52579236 390913.728800971663817.03647566391231.855579508
#Sta/Elev= 30
       0  912.71    22.1  903.79    62.2  879.04   118.5  853.02   154.6  838.32
   191.6  830.13  209.19813.3507     214  812.56  236.73813.3496   245.2  816.01
   252.4  816.44   307.8  815.14   432.8  815.78   450.7  820.43   475.7  820.24
   481.1  823.51   495.6  839.34   515.3  855.55   548.7  870.88   560.3  878.34
   578.1  893.99   595.1  905.25     615  912.21     661  933.87   709.5  962.27
   725.8  969.52   765.9   993.5     791  1003.4   820.6 1022.01   855.3 1034.54
#Mann= 7 ,-1,0
       0      .1       0     180     .06       0  209.19    .045       0
  236.73     .06       0  292.75      .1       0  402.75     .06       0
   516.5      .1       0
Bank Sta=209.19,236.73
XS Rating Curve= 0 ,0
Exp/Cntr(USF)=0,0
Exp/Cntr=0.3,0.1

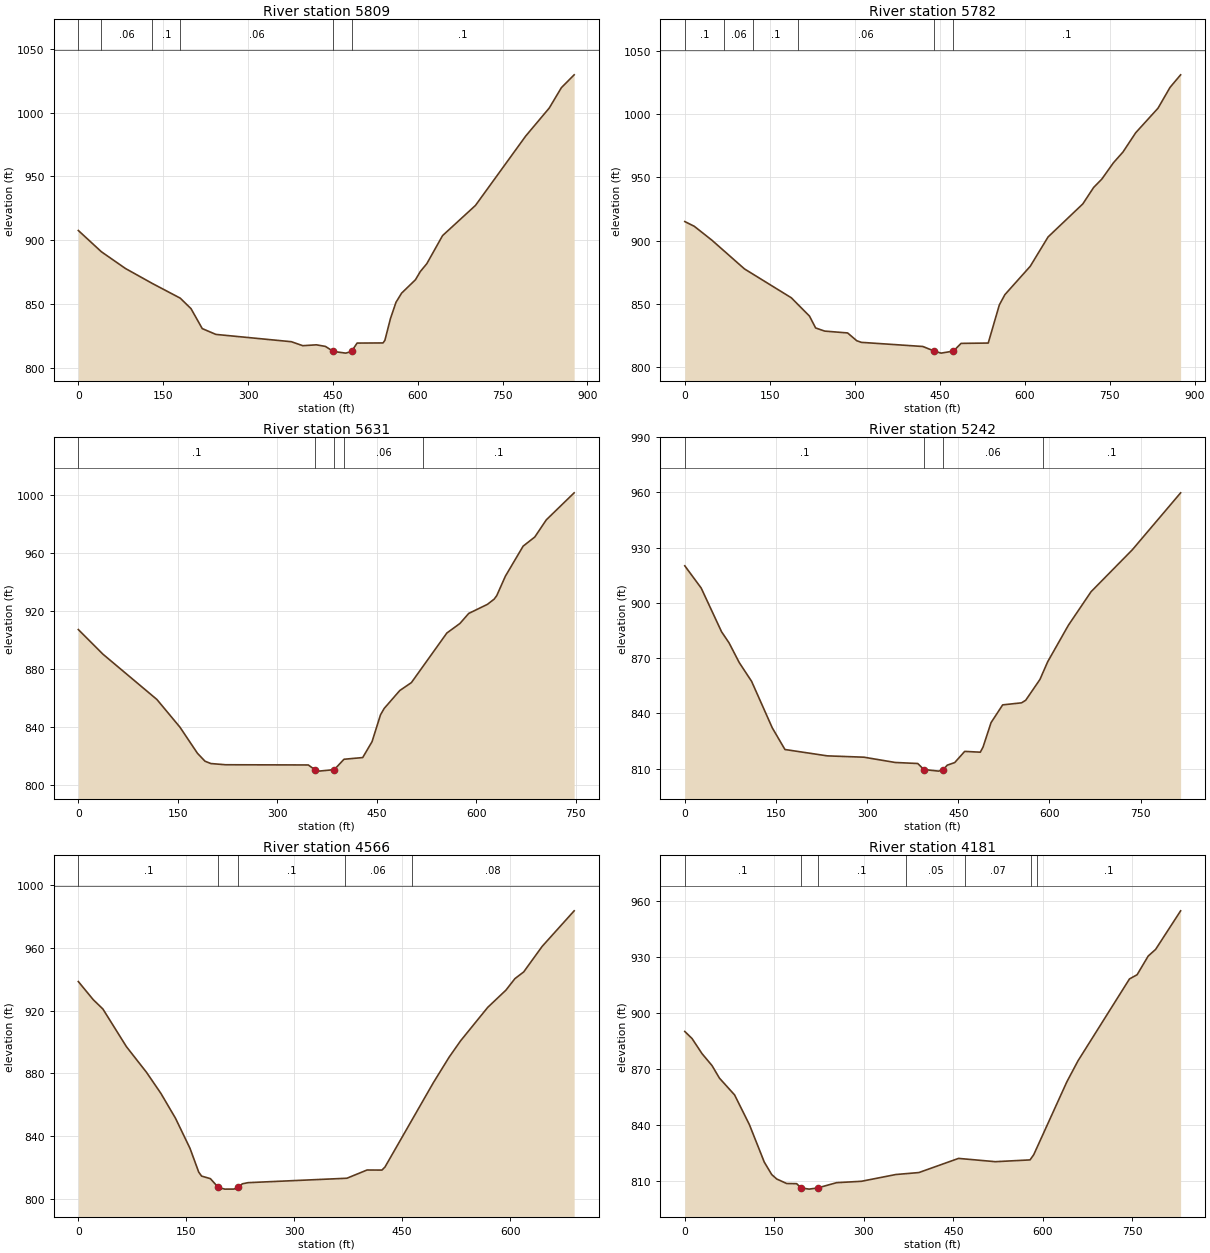
Type RM Length L Ch R = 1 ,5809    ,27.9,27.2,25.2
XS GIS Cut Line= 5
1663192.48981545390574.4290380541663381.13453273390750.878659319
1663364.77871272390894.3460325141663364.69289611391006.448243587
1663575.99239173  391300.2601553
#Sta/Elev= 30
       0  907.52    40.8  890.84    83.3  877.73   130.9  865.97   180.2  854.46
   199.3  846.19   219.1  830.58   243.2  826.02   376.7  820.29   396.9  817.17
   420.9  817.85   436.9  816.61  450.86812.6574   472.9  811.34  483.06812.6577
   492.9  819.22   538.8  819.33     542  821.33   551.9  838.45   561.7  851.23
   571.6  858.39   596.1   868.9   604.7  875.34   616.2  881.51     644   903.5
   702.2  927.18     791  981.58   832.7 1003.59   854.1 1019.53   876.7 1029.62
#Mann= 6 ,-1,0
       0      .1       0    40.8     .06       0   130.9      .1       0
   180.2     .06       0  450.86    .045       0  483.06      .1       0
Bank Sta=450.86,483.06
XS Rating Curve= 0 ,0
Exp/Cntr(USF)=0,0
Exp/Cntr=0.3,0.1

Type RM Length L Ch R = 1 ,5782    ,158.6,151,143.2
XS GIS Cut Line= 5
1663167.32768302390588.6693050551663344.42735906390736.700363254
1663328.79448308390849.1148470881663343.68380034391023.725931308
1663549.65481538391313.054534237
#Sta/Elev= 30
       0  915.13    16.7   911.4    47.9  900.35   105.3  877.65   187.9  854.82
     220   840.3   230.8  830.94   246.8  828.45   287.2     827   303.3  820.85
   311.4  819.55     420  816.27   440.1  812.65   452.1  811.02  473.86 812.632
   487.4  818.73   535.3  818.99   554.9  849.19   564.7  857.31   609.4  879.74
   640.9  902.97   702.2  929.12   721.2  942.09   735.6  948.69   756.2  961.66
   772.9   970.1   795.5  985.43   834.8 1004.82     856  1021.3   874.7 1031.24
#Mann= 6 ,-1,0
       0      .1       0      70     .06       0     120      .1       0
     200     .06       0   440.1    .045       0  473.86      .1       0
Bank Sta=440.1,473.86
XS Rating Curve= 0 ,0
Exp/Cntr(USF)=0,0
Exp/Cntr=0.3,0.1

Type RM Length L Ch R = 1 ,5631    ,394.1,388.6,382.3
XS GIS Cut Line= 2
1663014.04047368 390719.71648517 1663406.5770196391355.896404422
#Sta/Elev= 30
       0  907.36      37  890.44   118.5  859.19   153.3  840.09   179.6  822.15
     191   816.7   199.8   815.1   221.9  814.27   346.7  814.12  356.53810.8917
   362.5  809.88   385.8  810.89   400.5  818.05   428.7  819.22   442.8  830.16
   455.5  848.58     461  852.98   484.6  865.37   502.1  870.82   555.6  904.98
   575.3  911.55   588.5  918.44   616.7   924.7     627  928.35   630.8  930.73
   643.8  944.09   670.6   964.8   688.1  971.06   705.5  982.89   747.5  1001.5
#Mann= 5 ,-1,0
       0      .1       0  356.53    .045       0   385.8      .1       0
     400     .06       0     520      .1       0
Bank Sta=356.53,385.8
XS Rating Curve= 0 ,0
Exp/Cntr(USF)=0,0
Exp/Cntr=0.3,0.1

Type RM Length L Ch R = 1 ,5242    ,681.4,676.5,667.4
XS GIS Cut Line= 4
1662673.23304525390946.6634373411662732.00775548391142.860926906
1662952.12874211 391306.387808271663182.41986773391552.129380317
#Sta/Elev= 30
       0  920.17      27  908.08    60.4   884.4    72.9  878.26    89.6   867.6
   109.9  857.42   143.9  832.17   164.8  820.38   234.5  816.93   294.7  816.21
   346.2  813.34   383.3  812.78  393.35 809.495   417.7  808.64  425.28 809.498
   431.9  811.89   444.1  813.28   460.5  819.36   486.2  818.93   490.7   821.7
   503.9  834.99     523  844.63   554.1  845.74   560.9  847.13   584.3  858.42
   597.1  868.07   631.1  887.86   668.4  906.08   736.4  928.91   815.8  959.82
#Mann= 4 ,-1,0
       0      .1       0  393.35    .045       0  425.28     .06       0
  589.03      .1       0
Bank Sta=393.35,425.28
XS Rating Curve= 0 ,0
Exp/Cntr(USF)=0,0
Exp/Cntr=0.3,0.1

Type RM Length L Ch R = 1 ,4566    ,365.3,384.9,397.7
XS GIS Cut Line= 3
1662370.31023734391739.055876898 1662779.9144466391794.344272041
1663042.51675325391878.361813712
#Sta/Elev= 30
       0  938.64    20.7  927.08    34.1  921.13    66.9  897.02    94.7   880.7
   114.8  867.18     135  851.37   155.2  832.12   167.3  816.95   171.3  814.41
   183.5  812.78  194.51807.1806   203.6  806.09   216.3  806.12  222.15807.1807
   227.9  809.48   235.9  810.22   373.2  813.04   401.2   818.3   421.9  818.25
   426.1  820.19   493.3  874.03   515.2  890.32   531.1  900.75   568.9  922.16
   594.1  933.11   606.7  940.52   618.9  944.81   644.5  961.08     689  983.81
#Mann= 5 ,-1,0
       0      .1       0  194.51    .045       0  222.15      .1       0
     370     .06       0  463.32     .08       0
Bank Sta=194.51,222.15
XS Rating Curve= 0 ,0
Exp/Cntr(USF)=0,0
Exp/Cntr=0.3,0.1

Type RM Length L Ch R = 1 ,4181    ,543.7,543.9,542.5
XS GIS Cut Line= 3
1662356.13953672391884.8631917411662495.83095233392355.084241145
1662618.36575892392672.575856119
#Sta/Elev= 30
       0  890.07    12.2  886.27    28.9  878.18    45.6   871.8    58.1  865.04
    83.4  856.08   108.2  840.17   133.2  820.04   145.7  813.35   154.1  810.98
   170.7  808.57   187.4  808.49  194.77 806.203   208.3  805.56  222.74806.2023
   254.2  809.01   295.9  809.76   353.6  813.39   392.2  814.44   458.7  822.03
   520.5  820.27   578.5  821.23   584.7  824.04   640.4  863.24   658.9  874.37
   745.1  918.23   757.9   920.5   776.5  930.52   788.9  934.08   830.8  954.75
#Mann= 7 ,-1,0
       0      .1       0  194.77    .045       0  222.74      .1       0
     370     .05       0     470     .07       0  580.53     .06       0
  590.53      .1       0
Bank Sta=194.77,222.74
XS Rating Curve= 0 ,0
Exp/Cntr(USF)=0,0
Exp/Cntr=0.3,0.1

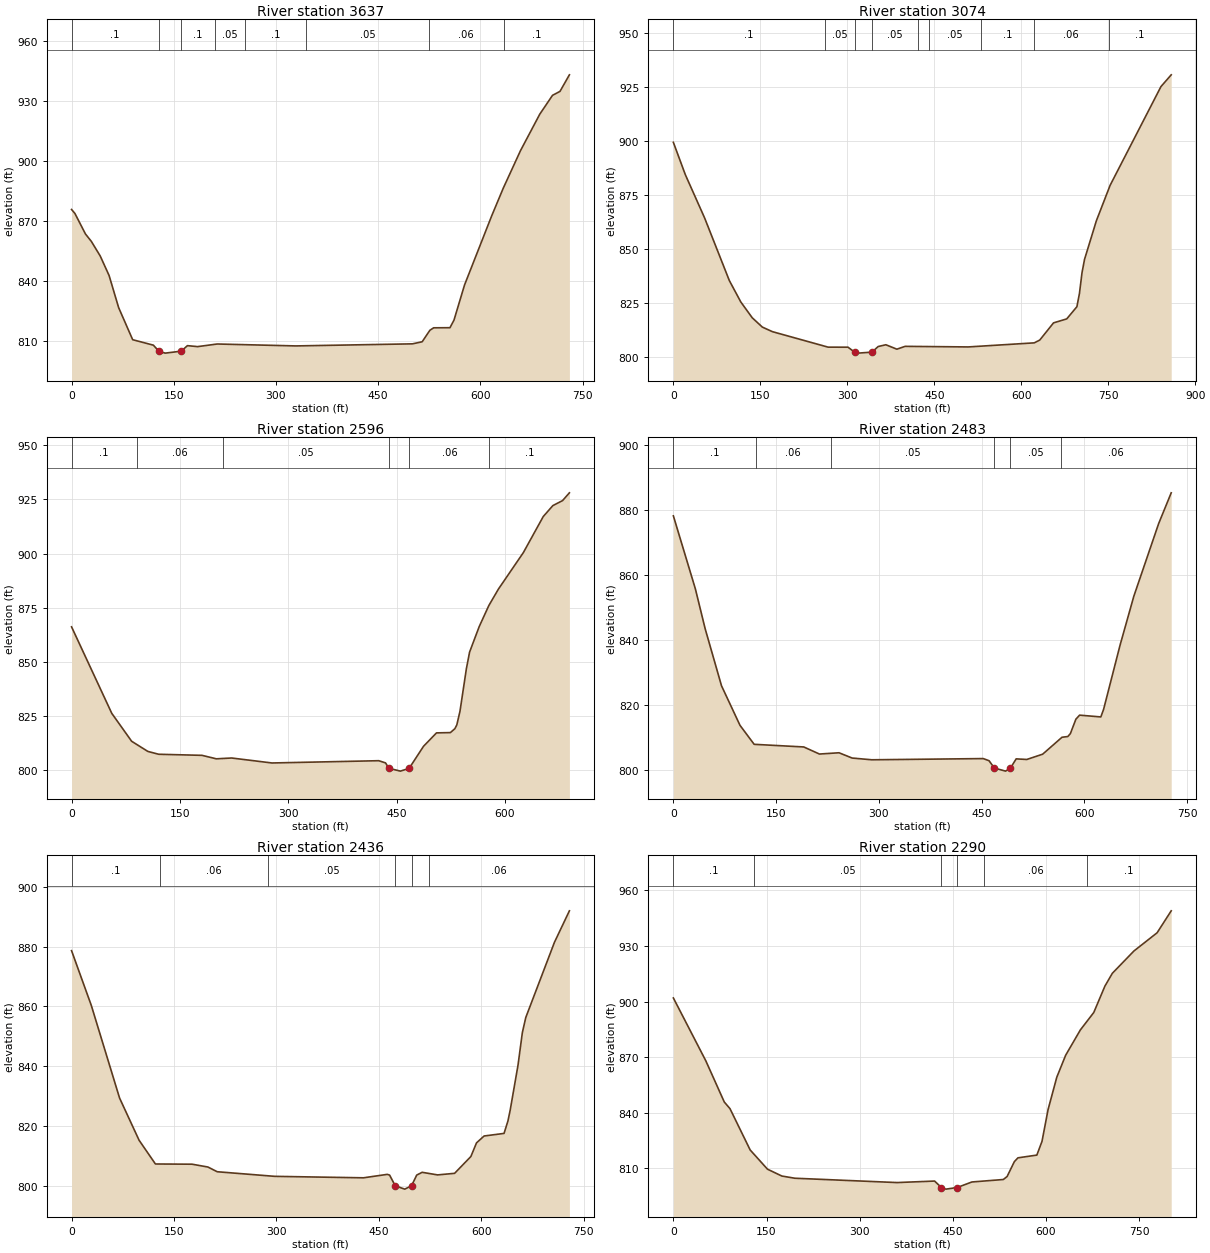
Type RM Length L Ch R = 1 ,3637    ,571.6,563.3,552.5
XS GIS Cut Line= 3
1661936.60639355392241.6694680621662026.54409072392458.009653746
1662390.22825182392795.815793383
#Sta/Elev= 30
       0  875.56     4.9  873.59    20.4  863.32    29.1  859.58    42.1  852.29
    55.1  842.54    69.1   826.5    89.7  810.45   120.1  807.72  128.12 804.723
   137.4  803.74  160.95 804.721   170.1  807.48     185  806.99   213.8   808.3
   329.2  807.34   500.4  808.38   514.6  809.42   525.9  815.15   531.5   816.4
   555.4  816.45   561.3  820.24   576.8  837.83   616.5  872.25   633.4  886.04
   658.9  904.97   687.2   923.2   705.9  932.63   716.9  934.62   730.7  942.89
#Mann= 8 ,-1,0
       0      .1       0  128.12    .045       0  160.95      .1       0
     210     .05       0  254.29      .1       0  344.29     .05       0
  524.29     .06       0  634.29      .1       0
Bank Sta=128.12,160.95
XS Rating Curve= 0 ,0
Exp/Cntr(USF)=0,0
Exp/Cntr=0.3,0.1

Type RM Length L Ch R = 1 ,3074    ,466.9,477.5,473.2
XS GIS Cut Line= 4
1661413.39563829392570.7269530061661514.08331099392669.744273212
1661952.68466394 392948.963812451662036.07319337393128.004398718
#Sta/Elev= 30
       0  899.46    20.6   884.5    53.9  864.42    96.5  835.42   116.3  825.49
   136.1  818.13   153.4  813.85   170.8  811.72   266.9  804.54   301.2  804.52
  312.62802.2253   318.6  801.77  342.43802.2263   353.3  804.83   366.5  805.65
   385.5   803.6   399.7  804.91   508.7  804.64   622.5  806.53     632  807.83
   655.7  815.79   678.5  817.64     696  823.27   700.4  829.39   704.8  838.98
   709.2  845.25   729.6  863.11   753.3  879.54     841  925.31   858.7  930.76
#Mann= 9 ,-1,0
       0      .1       0  261.22     .05       0  312.62    .045       0
  342.43     .05       0  421.22      .1       0  441.22     .05       0
  531.22      .1       0  621.22     .06       0  751.15      .1       0
Bank Sta=312.62,342.43
XS Rating Curve= 0 ,0
Exp/Cntr(USF)=0,0
Exp/Cntr=0.3,0.1

Type RM Length L Ch R = 1 ,2596    ,111.1,113.7,113.4
XS GIS Cut Line= 3
 1661283.5296039392908.6531675281661698.83025073393219.328337576
1661852.77041908393293.097892636
#Sta/Elev= 30
       0  866.08    55.7  826.06    83.2  813.15   105.6  808.46   120.6  807.14
   180.6  806.64   200.5  805.03   221.6  805.41   277.5  803.11   425.3  804.16
   434.7  803.15  439.44800.6472   455.3  799.34  467.46800.6457   487.3  810.82
   505.3  817.03   524.5  817.16   530.7  818.96   533.4   820.7   537.8  827.03
   546.7  846.79   551.1  854.39   564.4  866.18   577.7   875.9     591  883.53
   625.5   900.4   653.1   917.1   666.4  922.16   679.8  924.47   689.3  928.07
#Mann= 6 ,-1,0
       0      .1       0      90     .06       0     210     .05       0
  439.44    .045       0  467.46     .06       0  578.65      .1       0
Bank Sta=439.44,467.46
XS Rating Curve= 0 ,0
Exp/Cntr(USF)=0,0
Exp/Cntr=0.3,0.1

Type RM Length L Ch R = 1 ,2483    ,45.6,46.5,47.2
XS GIS Cut Line= 6
1661257.15892497392928.9181514221661481.91993686393074.738710361
1661493.98028384393188.7638090791661593.60684938393279.316413087
1661586.40527947393351.0376974841661722.35828179393365.290834824
#Sta/Elev= 30
       0  878.17    32.1  855.72    46.4  843.44    70.3  825.87    97.3  813.69
     118  807.85   190.4  807.04   213.3  804.86   241.9  805.25     261  803.63
   289.7  803.09   452.5  803.46     461   802.8  468.68800.5541   485.1   799.6
   492.3  800.55   500.6  803.37   516.1  803.19   539.3  804.82   567.5  810.02
     576  810.25   579.7  811.13   587.8  815.59   593.2  816.83   624.2  816.28
   628.2  818.57   652.3  838.37   672.4  853.43   708.6  875.76     727  885.26
#Mann= 6 ,-1,0
       0      .1       0     120     .06       0     230     .05       0
  468.68    .045       0   492.3     .05       0  565.94     .06       0
Bank Sta=468.68,492.3
XS Rating Curve= 0 ,0
Exp/Cntr(USF)=0,0
Exp/Cntr=0.3,0.1

Type RM Length L Ch R = 1 ,2436    ,150.1,146.3,144.6
XS GIS Cut Line= 6
1661245.09857799392947.5568694821661444.64250074393076.931500721
1661449.02808146393193.1493897991661554.90521758393310.008076361
1661547.70364766393381.729360757 1661633.2224717393496.850854656
#Sta/Elev= 30
       0  878.65    28.9  860.36    70.3  829.41    98.9   815.3   122.8  807.37
   176.4   807.3   199.6  806.36   213.3  804.78   297.5  803.24   427.4  802.75
   462.3   803.9   465.7  803.66  473.99 800.071   487.9  798.97  497.87800.0715
   505.4  803.66   513.4  804.59     536  803.72   560.9  804.25   584.7  809.86
     593  814.43   604.1  816.72   633.3  817.59     639  821.74   642.3  825.37
   653.7  840.32   660.1  851.26   665.1   856.3   707.1  881.44     729  891.96
#Mann= 6 ,-1,0
       0      .1       0     130     .06       0  287.81     .05       0
  473.99    .045       0  497.87     .05       0  523.42     .06       0
Bank Sta=473.99,497.87
XS Rating Curve= 0 ,0
Exp/Cntr(USF)=0,0
Exp/Cntr=0.3,0.1

Type RM Length L Ch R = 1 ,2290    ,142.8,137.3,135.6
XS GIS Cut Line= 3
1661045.40678207393167.7371327291661534.03193247393454.283120978
1661708.56688974393612.107284468
#Sta/Elev= 30
       0  901.94    52.3  867.99      82  845.79    91.2  842.19   123.7   819.9
   151.6  809.53   174.7  805.84   195.5  804.65   360.2  802.31   420.7  803.12
  431.79799.6078     439  798.77  456.82799.6062   480.8  802.63   531.4  803.96
   537.5  805.58   549.2  813.62     555  815.66   585.4  817.14   593.7  824.56
   603.5  841.74   617.5  859.16   631.8  871.03   655.5   884.7   677.1  894.11
     695  908.33     707  915.26   741.8  927.31   779.1  937.13   801.8  948.97
#Mann= 6 ,-1,0
       0      .1       0     130     .05       0  431.79    .045       0
  456.82     .05       0     500     .06       0  666.45      .1       0
Bank Sta=431.79,456.82
XS Rating Curve= 0 ,0
Exp/Cntr(USF)=0,0
Exp/Cntr=0.3,0.1

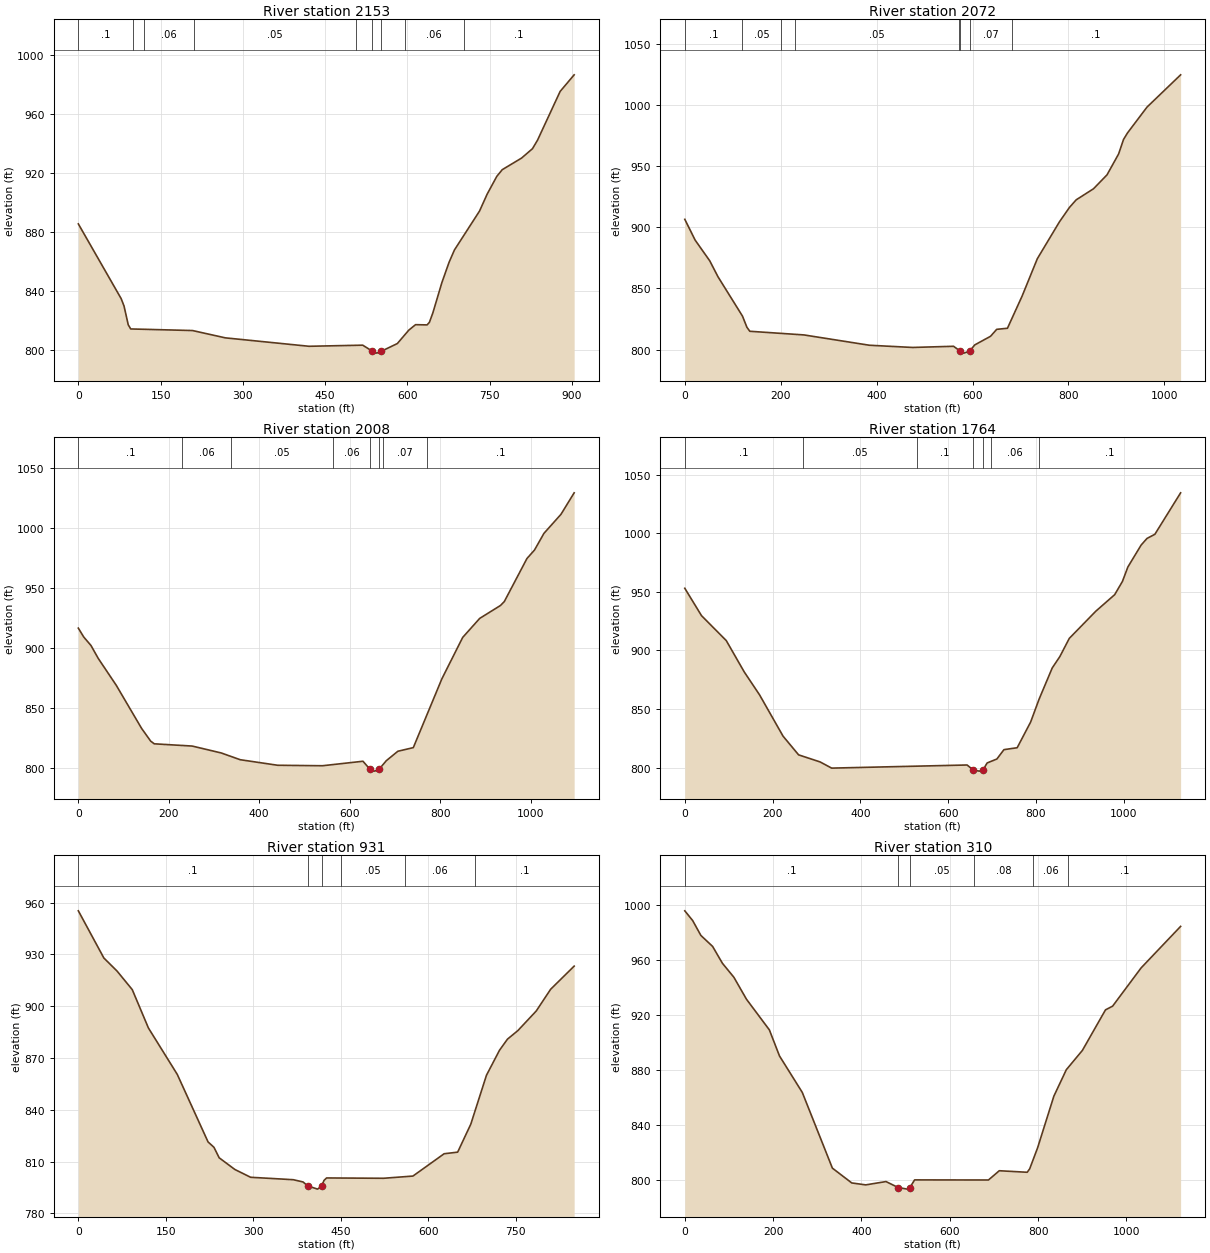
Type RM Length L Ch R = 1 ,2153    ,80.8,81,81.6
XS GIS Cut Line= 4
1661010.40233076393228.8702154781661099.21034034393436.088904496
1661498.29818585393556.6923742941661726.34838329393684.970610353
#Sta/Elev= 30
       0  885.34      78  834.64    83.3  829.61      91  816.81    95.5  813.99
   208.2  812.91     268  807.94   420.6  802.22   518.5  802.97  536.26798.8441
     544  797.57  552.45798.8427   581.6  804.06   602.5  813.17   614.8  816.89
   635.9  816.74   640.1  818.49   646.5  825.03   662.8  845.44   675.9  859.22
   685.7  867.62   731.5  894.08   745.4  905.56   762.9  917.59   772.9  922.17
   808.1  930.04     828  936.42   837.2  942.19   878.5  975.35     904  986.59
#Mann= 9 ,-1,0
       0      .1       0     100     .05       0     120     .06       0
     210     .05       0  505.45     .07       0  536.26    .045       0
  552.45     .07       0  595.45     .06       0  702.36      .1       0
Bank Sta=536.26,552.45
XS Rating Curve= 0 ,0
Exp/Cntr(USF)=0,0
Exp/Cntr=0.3,0.1

Type RM Length L Ch R = 1 ,2072    ,63.6,63.7,63.6
XS GIS Cut Line= 5
1660978.55125336393212.605029621 1661073.0520754  393437.9466513
1661176.98286343393527.365209348 1661473.7100671393640.982795742
1661794.01935865393738.038991076
#Sta/Elev= 30
       0  906.55    21.6  889.53      52  872.63    69.3  859.52   120.3  827.38
   129.5  818.28   135.6  814.98   248.4     812   384.8  803.56   474.8  801.75
   560.4   802.7  574.75798.6629   581.8  797.11  593.68798.6611   604.7  803.85
   637.5  810.87   650.4  816.57   672.8  817.45   703.5  843.88   735.1  874.34
   781.1  904.42     802  916.23   816.2  922.51   852.2  931.53   880.4  942.92
   904.6  960.03   914.9  971.93   923.2  977.24   963.8  998.34  1033.9 1024.74
#Mann= 8 ,-1,0
       0      .1       0     120     .05       0     200     .06       0
     230     .05       0  571.46     .07       0  574.75    .045       0
  593.68     .07       0  681.46      .1       0
Bank Sta=574.75,593.68
XS Rating Curve= 0 ,0
Exp/Cntr(USF)=0,0
Exp/Cntr=0.3,0.1

Type RM Length L Ch R = 1 ,2008    ,243.2,244,244.5
XS GIS Cut Line= 5
1660732.08151246393492.2701877051661039.09349901  393492.9184762
1661143.02428704393582.3370342491661439.75149071393695.954620642
1661760.06078226393793.010815976
#Sta/Elev= 30
       0  916.46      12  909.05      28  901.98      44  891.25      84  868.71
     140  832.78     160  822.21     168  819.96   251.8  818.09     316  812.34
     358   806.7   440.8  802.07   539.8  801.67   629.5  805.42  645.35798.5568
   655.2  797.18  664.77798.5562   680.9  805.82   706.6  813.75   740.8  816.79
     804  874.22     850  908.72   887.6  924.58   933.6  935.38     942  938.62
   992.1  974.54  1008.8  981.62  1029.7  995.54  1067.3  1011.4  1096.5 1029.35
#Mann= 8 ,-1,0
       0      .1       0     230     .06       0  337.01     .05       0
  564.12     .06       0  645.35    .045       0  664.77     .06       0
  674.12     .07       0  771.85      .1       0
Bank Sta=645.35,664.77
XS Rating Curve= 0 ,0
Exp/Cntr(USF)=0,0
Exp/Cntr=0.3,0.1

Type RM Length L Ch R = 1 ,1764    ,826.1,833,827.1
XS GIS Cut Line= 4
 1660602.2830455393652.6285482581660819.26489884   393679.271866
1661306.03032631393910.9505502211661651.64801466394049.387701224
#Sta/Elev= 30
       0  952.95    38.1  929.59    94.5  908.32   135.4   881.6   170.3  862.06
     224  826.73   259.4   810.8   308.2  804.79   334.7  799.49   643.4  802.15
  657.41797.8051   671.4  796.92  679.42797.8071   689.1   803.9   711.3  807.28
   727.4  815.26   757.5  816.88   788.2  838.82   807.3   858.2   837.4  884.97
   854.7  894.64   876.3   910.2   936.6  933.35   979.7  947.49   997.4   958.8
  1009.7  971.05    1040  989.82  1053.3  995.46  1071.3  999.02    1130  1034.4
#Mann= 7 ,-1,0
       0      .1       0  268.61     .05       0  528.61      .1       0
  657.41    .045       0  679.42      .1       0  698.61     .06       0
   807.7      .1       0
Bank Sta=657.41,679.42
XS Rating Curve= 0 ,0
Exp/Cntr(USF)=0,0
Exp/Cntr=0.3,0.1

Type RM Length L Ch R = 1 ,931     ,610.2,621,620.7
XS GIS Cut Line= 2
1660557.13073117393907.059336433 1661313.9043337394294.877514845
#Sta/Elev= 30
       0   955.2    43.8  927.89    66.3  920.37    92.5  909.58   120.2  887.38
   169.7  860.51   222.5  821.41   232.6  818.31   241.6  812.22   268.5  805.46
   295.5  800.95   368.8  799.54   385.4  798.24  393.56 795.942   410.4  794.09
   417.4795.9411   421.4  799.15   425.8  800.56   523.4  800.37   573.9  801.65
   627.4  814.57   650.6   815.5   673.1  831.67     700  860.01   722.4  874.51
     736   880.9     754  885.91   785.4  897.23   810.1   909.8   850.4  923.19
#Mann= 6 ,-1,0
       0      .1       0  393.56    .045       0   417.4      .1       0
     450     .05       0     560     .06       0     680      .1       0
Bank Sta=393.56,417.4
XS Rating Curve= 0 ,0
Exp/Cntr(USF)=0,0
Exp/Cntr=0.3,0.1

Type RM Length L Ch R = 1 ,310     ,312.1,310,303
XS GIS Cut Line= 4
1660347.95686613394101.9921532681660494.04466819394310.312304214
1660844.97133759 394685.37678686 1661196.9888287394728.171266484
#Sta/Elev= 30
       0  995.59    17.8  988.52    36.4  977.69      63  969.68    85.2   957.4
   111.1  947.26   139.6  931.27   191.5  908.93   214.4  889.97     266  863.44
   334.2   808.3     378  797.53   409.7  796.11   455.6  798.53  483.08794.1869
     504  793.02  509.61794.1851   520.4  799.74   687.6  799.67   712.1  806.41
   775.3  805.29   780.9  807.77   798.9  823.13   835.7   860.7   863.9  879.94
   900.2  893.96   952.6  923.51   968.7   926.2  1033.2  954.03  1122.7  984.27
#Mann= 6 ,-1,0
       0      .1       0  483.08    .045       0  509.61     .05       0
  654.44     .08       0  788.08     .06       0  868.08      .1       0
Bank Sta=483.08,509.61
XS Rating Curve= 0 ,0
Exp/Cntr(USF)=0,0
Exp/Cntr=0.3,0.1

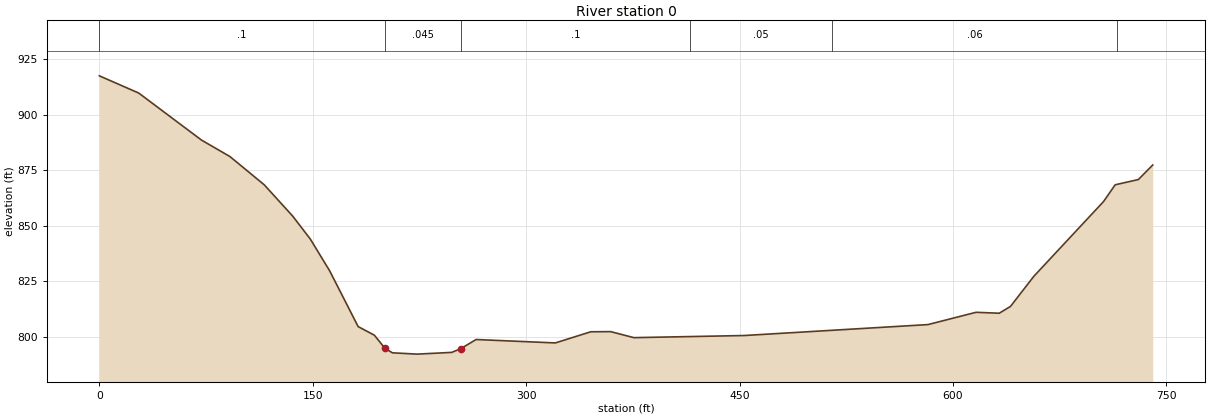
Type RM Length L Ch R = 1 ,0       ,,,
XS GIS Cut Line= 4
1660348.17881228394332.870394143 1660339.3668296394487.542015026
1660458.61698271394648.322011999 1660384.6258555395026.495782998
#Sta/Elev= 30
       0  917.51    27.7  909.75    71.8  888.58    91.8  881.16   115.9  868.44
   135.9  854.35   148.3     844   161.9  829.69   181.9   804.6   193.3  800.72
   200.8 794.773     206  792.78   223.3  792.19   247.7  792.97  254.15 794.689
   264.8  798.77   320.5  797.23   345.4  802.25   359.4  802.32   375.7  799.61
   453.1  800.56   582.4  805.49   616.2  811.02   632.5  810.61   640.4  813.66
   656.9  827.29   705.8  860.88     714  868.44   730.3  870.81   740.4  877.36
#Mann= 6 ,-1,0
       0      .1       0   200.8    .045       0  254.15      .1       0
   415.1     .05       0   515.1     .06       0   715.1      .1       0
Bank Sta=200.8,254.15
XS Rating Curve= 0 ,0
Exp/Cntr=0.3,0.1
LCMann Table=0

Chan Stop Cuts=-1
Use User Specified Reach Order=0
Composite Channel Slope=5